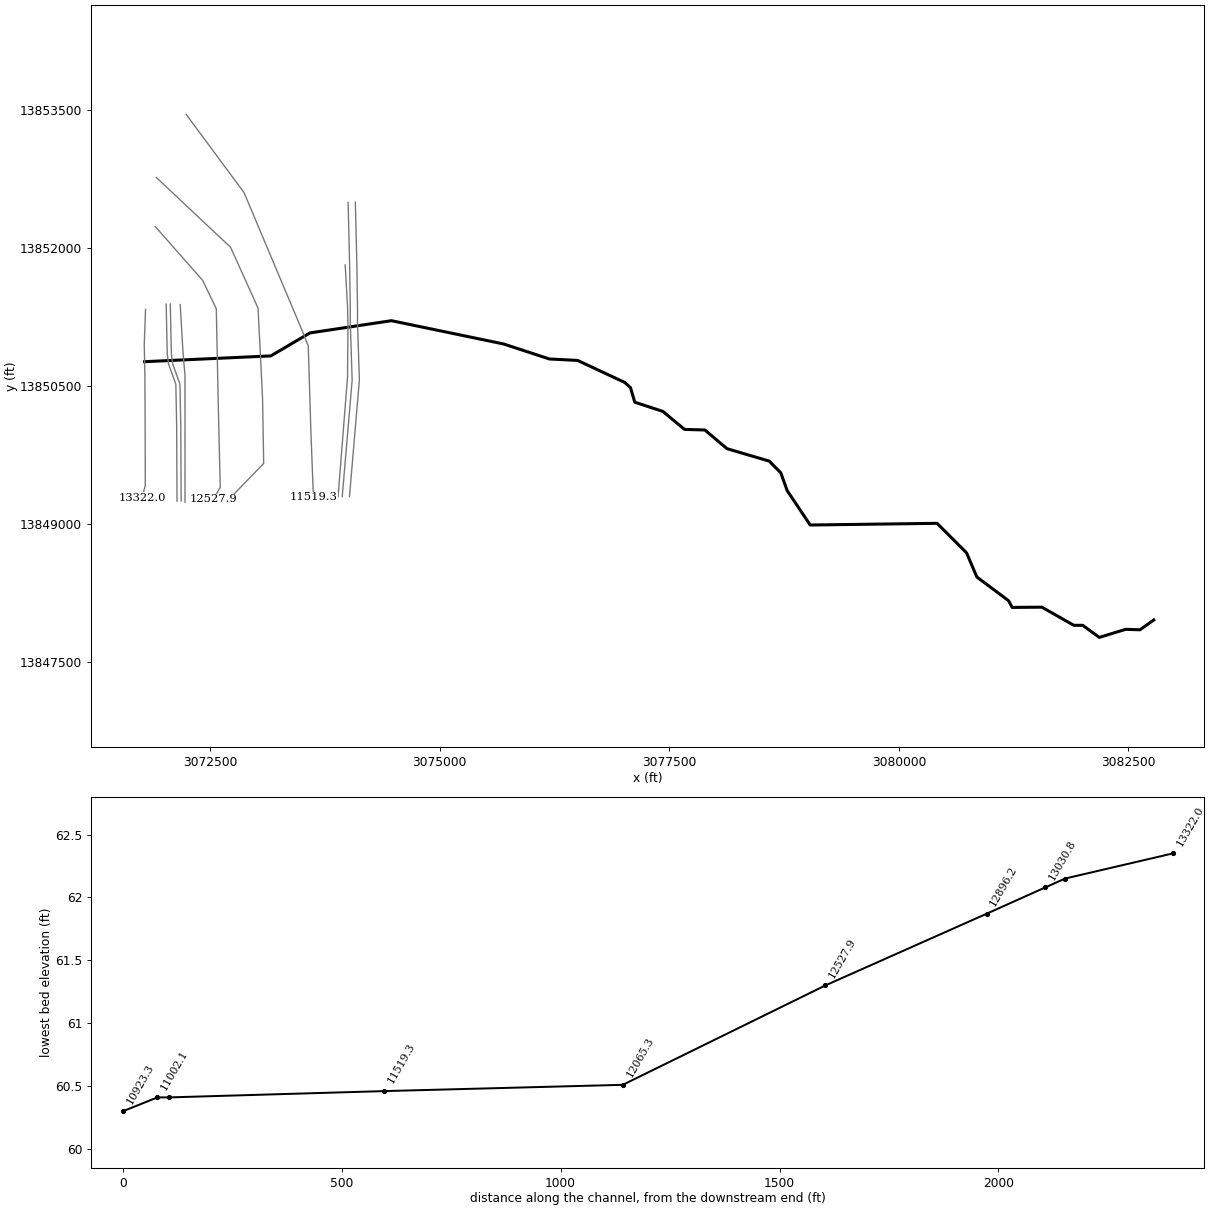
--- W140-01-00.PRJ (project) ---

Proj Title=W140-01-00
Current Plan=p02
Default Exp/Contr=.3,.1
English Units
Geom File=g01
Flow File=f01
Flow File=f02
Plan File=p01
Plan File=p02
Y Axis Title=Elevation
X Axis Title(PF)=Main Channel Distance
X Axis Title(XS)=Station
BEGIN DESCRIPTION:
Buffalo Bayou Watershed
Briar Branch
HCFCD Unit W140-01-00
Flood Hazard Model
10, 2, 1, 0.2% Event
Filename W140-01-00.prj
Prepared by:  Watershed Concepts  Date:
Reviewed by:                      Date:
STATUS FINAL
END DESCRIPTION:
DSS Export Rating Curves= 0
DSS Export Rating Curve Sorted= 0
DSS Export Volume Flow Curves= 0
DXF OffsetX= 0
DXF OffsetY= 0
DXF ScaleX= 1
DXF ScaleY= 10

--- W140-01-00.p02 (plan) ---

Plan Title=Floodway
Version=Version 3.0.1  Mar 2001
Short Identifier=Floodway0607
Geom File=g01
Flow File=f02
Subcritical Flow
K Sum by GR= 0
Std Step Tol= 0.01
Critical Tol= 0.01
Num of Std Step Trials= 20
Max Error Tol= 0.3
Flow Tol Ratio= 0.001
Split Flow NTrial= 30
Split Flow Tol= 0.02
Split Flow Ratio= 0.02
Log Output Level= 0
Friction Slope Method= 1
Unsteady Friction Slope Method= 2
Parabolic Critical Depth
Global Vel Dist= 0 , 0 , 0
Global Log Level= 0
CheckData=True
Encroach Param=-1 ,0,0, 2
Encroach River=W140-01-00
Encroach Reach=Reach - 1
Encroach Node=13322.0
       1 4973.26 5011.26
Encroach Node=13075.6
       1  4973.3  5011.3
Encroach Node=13053.2
       1  4973.3  5011.3
Encroach Node=13030.8
       1  4973.3  5011.3
Encroach Node=12896.2
       1  4981.4  5018.5
Encroach Node=12527.9
       1  4961.1  5021.1
Encroach Node=12065.3
       1  4981.4  5018.5
Encroach Node=11519.3
       1  4965.9  5022.5
Encroach Node=11029.3
       1  4976.6  5022.5
Encroach Node=11002.1
       1    4967    5032
Encroach Node=10962.7
       1    4967    5032
Encroach Node=10923.3
       1    4967    5032
Encroach Node=10764.8
       1  4964.5  5020.3
Encroach Node=10641.7
       1    4968    5028
Encroach Node=10599.6
       1    4968    5028
Encroach Node=10581.7
       1    4968    5028
Encroach Node=10563.8
       1  4978.2  5020.3
Encroach Node=10404.9
       1  4983.9  5016.4
Encroach Node=9889.4
       1  4983.9  5016.4
Encroach Node=9202.8
       1  4978.1  5029.7
Encroach Node=9132.0
       1  4978.1  5029.6
Encroach Node=9104.1
       1  4978.1  5029.6
Encroach Node=9076.2
       1  4978.1  5029.6
Encroach Node=8911.9
       1  4983.8  5018.2
Encroach Node=8753.8
       1  4983.8  5018.2
Encroach Node=8320.8
       1  4983.8  5018.2
Encroach Node=7945.8
       1  4981.3  5019.1
Encroach Node=7482.7
       1  4981.3  5013.6
Encroach Node=7444.9
       1  4981.3  5013.6
Encroach Node=7418.6
       1  4981.3  5013.6
Encroach Node=7392.3
       1  4981.3  5013.6
Encroach Node=7223.2
       1  4981.3  5013.6
Encroach Node=6508.1
       1  4979.9  5011.1
Encroach Node=5707.3
       1    4946  5036.3
Encroach Node=5602.5
       1    4946  5036.3
Encroach Node=5375.3
       1    4946  5036.3
Encroach Node=5148.1
       1    4946  5036.3
Encroach Node=4988.3
       1  4979.4  5023.4
Encroach Node=4200.8
       1  4979.4  5023.4
Encroach Node=3767.1
       1  4975.8  5070.5
Encroach Node=3368.2
       1  4975.8  5033.4
Encroach Node=2735.8
       1    4885  5020.3
Encroach Node=2065.5
       1  4981.3  5030.5
Encroach Node=1689.7
       1  4877.3  5052.7
Encroach Node=821.4
       1  4952.8  5022.2
Encroach Reach=W140-01-00_0008
Encroach Node=13322.0
       1 4973.26 5011.26
Encroach Node=13075.6
       1  4973.3  5011.3
Encroach Node=13053.2
       1  4973.3  5011.3
Encroach Node=13030.8
       1  4973.3  5011.3
Encroach Node=12896.2
       1  4981.4  5018.5
Encroach Node=12527.9
       1  4961.1  5021.1
Encroach Node=12065.3
       1  4981.4  5018.5
Encroach Node=11519.3
       1  4965.9  5022.5
Encroach Node=11029.3
       1  4976.6  5022.5
Encroach Node=11002.1
       1    4967    5032
Encroach Node=10962.7
       1    4967    5032
Encroach Node=10923.3
       1    4967    5032
Encroach Node=10764.8
       1  4964.5  5020.3
Encroach Node=10641.7
       1    4968    5028
Encroach Node=10599.6
       1    4968    5028
Encroach Node=10581.7
       1    4968    5028
Encroach Node=10563.8
       1  4978.2  5020.3
Encroach Node=10404.9
       1  4983.9  5016.4
Encroach Node=9889.4
       1  4983.9  5016.4
Encroach Node=9202.8
       1  4978.1  5029.7
Encroach Node=9132.0
       1  4978.1  5029.6
Encroach Node=9104.1
       1  4978.1  5029.6
Encroach Node=9076.2
       1  4978.1  5029.6
Encroach Node=8911.9
       1  4983.8  5018.2
Encroach Node=8753.8
       1  4983.8  5018.2
Encroach Node=8320.8
       1  4983.8  5018.2
Encroach Node=7945.8
       1  4981.3  5019.1
Encroach Node=7482.7
       1  4981.3  5013.6
Encroach Node=7444.9
       1  4981.3  5013.6
Encroach Node=7418.6
       1  4981.3  5013.6
Encroach Node=7392.3
       1  4981.3  5013.6
Encroach Node=7223.2
       1  4981.3  5013.6
Encroach Node=6508.1
       1  4979.9  5011.1
Encroach Node=5707.3
       1    4946  5036.3
Encroach Node=5602.5
       1    4946  5036.3
Encroach Node=5375.3
       1    4946  5036.3
Encroach Node=5148.1
       1    4946  5036.3
Encroach Node=4988.3
       1  4979.4  5023.4
Encroach Node=4200.8
       1  4979.4  5023.4
Encroach Node=3767.1
       1  4975.8  5070.5
Encroach Node=3368.2
       1  4975.8  5033.4
Encroach Node=2735.8
       1    4885  5020.3
Encroach Node=2065.5
       1  4981.3  5030.5
Encroach Node=1689.7
       1  4877.3  5052.7
Encroach Node=821.4
       1  4952.8  5022.2
Computation Interval=1HOUR
Output Interval=1HOUR
Run HTab= 0
Run UNet= 0
Run PostProcess= 0
UNET Theta= 1
UNET ZTol= 0.02
UNET ZSATol= 0.1
UNET MxIter= 20
UNET MaxInSteps= 20
UNET DtIC= 0
UNET DtMin= 0
UNET MaxCRTS= 20
UNET WFStab= 2
UNET SFStab= 1
UNET WFX= 1
UNET SFX= 1
UNET Convert EG Bridges=-1
UNET Use Existing IB Tables=-1
Instantaneous Interval=1HOUR
Write IC File= 0
IC Time=0
Write Velocity= 0
Write Detailed= 0

--- W140-01-00.p01 (plan) ---

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Plan Title=FEMA Effective June 2007
Program Version=3.13
Short Identifier=FEMAeff0607
Geom File=g01
Flow File=f01
Unsteady Bridges Friction Slope Method= 1
Encroach Param=-1 ,0,0, 0
UNET Theta Warmup= 1
UNET DSS MLevel= 4
UNET DZMax Abort= 100
UNET Froude Reduction=False
UNET Froude Limit= 1
UNET Froude Power= 10
Echo Input=False
Echo Output=False
Detailed Automatic Start=False, 10

--- W140-01-00.f02 (steady flow) ---

Flow Title=Floodway
Program Version=3.13
Number of Profiles= 2
Profile Names=1PCT_100_YR,1PCT_Floodway_100yrFW
River Rch & RM=W140-01-00,W140-01-00_0008       ,13322
    1088    1088
River Rch & RM=W140-01-00,W140-01-00_0008       ,10599.6
    1133    1133
River Rch & RM=W140-01-00,W140-01-00_0008       ,9889.4
    1203    1203
River Rch & RM=W140-01-00,W140-01-00_0008       ,9132
    1287    1287
River Rch & RM=W140-01-00,W140-01-00_0008       ,8320.8
    1365    1365
River Rch & RM=W140-01-00,W140-01-00_0008      ,7444.9
    1462    1462
River Rch & RM=W140-01-00,W140-01-00_0008      ,6508.1
    1553    1553
River Rch & RM=W140-01-00,W140-01-00_0008       ,5602.5
    1694    1694
River Rch & RM=W140-01-00,W140-01-00_0008       ,4200.8
    1792    1792
River Rch & RM=W140-01-00,W140-01-00_0008       ,3368.2
    1878    1878
River Rch & RM=W140-01-00,W140-01-00_0008       ,2065.5
    2013    2013
River Rch & RM=W140-01-00,W140-01-00_0008       ,821.4
    2142    2142
Boundary for River Rch & Prof#=W140-01-00,W140-01-00_0008       , 1
Up Type= 0
Dn Type= 3
Dn Slope=0.0063
Boundary for River Rch & Prof#=W140-01-00,W140-01-00_0008       , 2
Up Type= 0
Dn Type= 1
Dn Known WS=36.82
DSS Import GetInterval= 0
DSS Import GetPeak= 0
DSS Import FillOption= 0

--- W140-01-00.f01 (steady flow) ---

Flow Title=FEMA Effective June 2007
Program Version=3.13
Number of Profiles= 4
Profile Names=10PCT_10yr,2PCT_50yr,1PCT_100yr,0.2PCT_500yr
River Rch & RM=W140-01-00,W140-01-00_0008 ,13322
     589     912    1088    1642
River Rch & RM=W140-01-00,W140-01-00_0008 ,10599.6
     613     950    1133    1709
River Rch & RM=W140-01-00,W140-01-00_0008 ,9889.4
     651    1009    1203    1812
River Rch & RM=W140-01-00,W140-01-00_0008 ,9132
     696    1079    1287    1937
River Rch & RM=W140-01-00,W140-01-00_0008 ,8320.8
     738    1145    1365    2053
River Rch & RM=W140-01-00,W140-01-00_0008 ,7444.9
     790    1225    1462    2195
River Rch & RM=W140-01-00,W140-01-00_0008 ,6508.1
     840    1302    1553    2330
River Rch & RM=W140-01-00,W140-01-00_0008 ,5602.5
     916    1420    1694    2538
River Rch & RM=W140-01-00,W140-01-00_0008 ,4200.8
     969    1502    1792    2683
River Rch & RM=W140-01-00,W140-01-00_0008 ,3368.2
    1015    1574    1878    2810
River Rch & RM=W140-01-00,W140-01-00_0008 ,2065.5
    1088    1687    2013    3010
River Rch & RM=W140-01-00,W140-01-00_0008 ,821.4
    1158    1795    2142    3200
Boundary for River Rch & Prof#=W140-01-00,W140-01-00_0008 , 1
Up Type= 0
Dn Type= 3
Dn Slope=0.0063
Boundary for River Rch & Prof#=W140-01-00,W140-01-00_0008 , 2
Up Type= 0
Dn Type= 3
Dn Slope=0.0063
Boundary for River Rch & Prof#=W140-01-00,W140-01-00_0008 , 3
Up Type= 0
Dn Type= 3
Dn Slope=0.0063
Boundary for River Rch & Prof#=W140-01-00,W140-01-00_0008 , 4
Up Type= 0
Dn Type= 3
Dn Slope=0.0063
DSS Import GetInterval= 0
DSS Import GetPeak= 0
DSS Import FillOption= 0

--- W140-01-00.g01 (geometry) ---

Geom Title=W140-01-00 June 2007
Version=Version 3.0.1  Mar 2001

River Reach=W140-01-00      ,W140-01-00_0008
Reach XY= 30
      3071788.19     13850766.26      3073162.25       13850829.
      3073588.25       13851079.        3074476.       13851212.
      3075696.25       13850959.       3076195.3     13850795.72
      3076502.41     13850779.95      3077016.21     13850540.18
      3077078.49     13850484.12       3077125.2     13850325.31
      3077430.37     13850225.67      3077667.02     13850029.49
      3077888.11     13850023.26       3078129.5       13849820.
      3078588.25       13849685.      3078714.75       13849558.
       3078784.5       13849364.      3079034.96     13848989.67
      3080416.63     13849008.02      3080737.75      13848686.9
      3080849.66     13848424.16      3081195.11     13848166.29
      3081234.03     13848093.31      3081557.41     13848096.08
      3081905.47     13847898.69      3082002.79     13847898.69
      3082182.81     13847767.32      3082469.88      13847854.9
      3082625.57     13847850.03       3082776.4     13847957.07

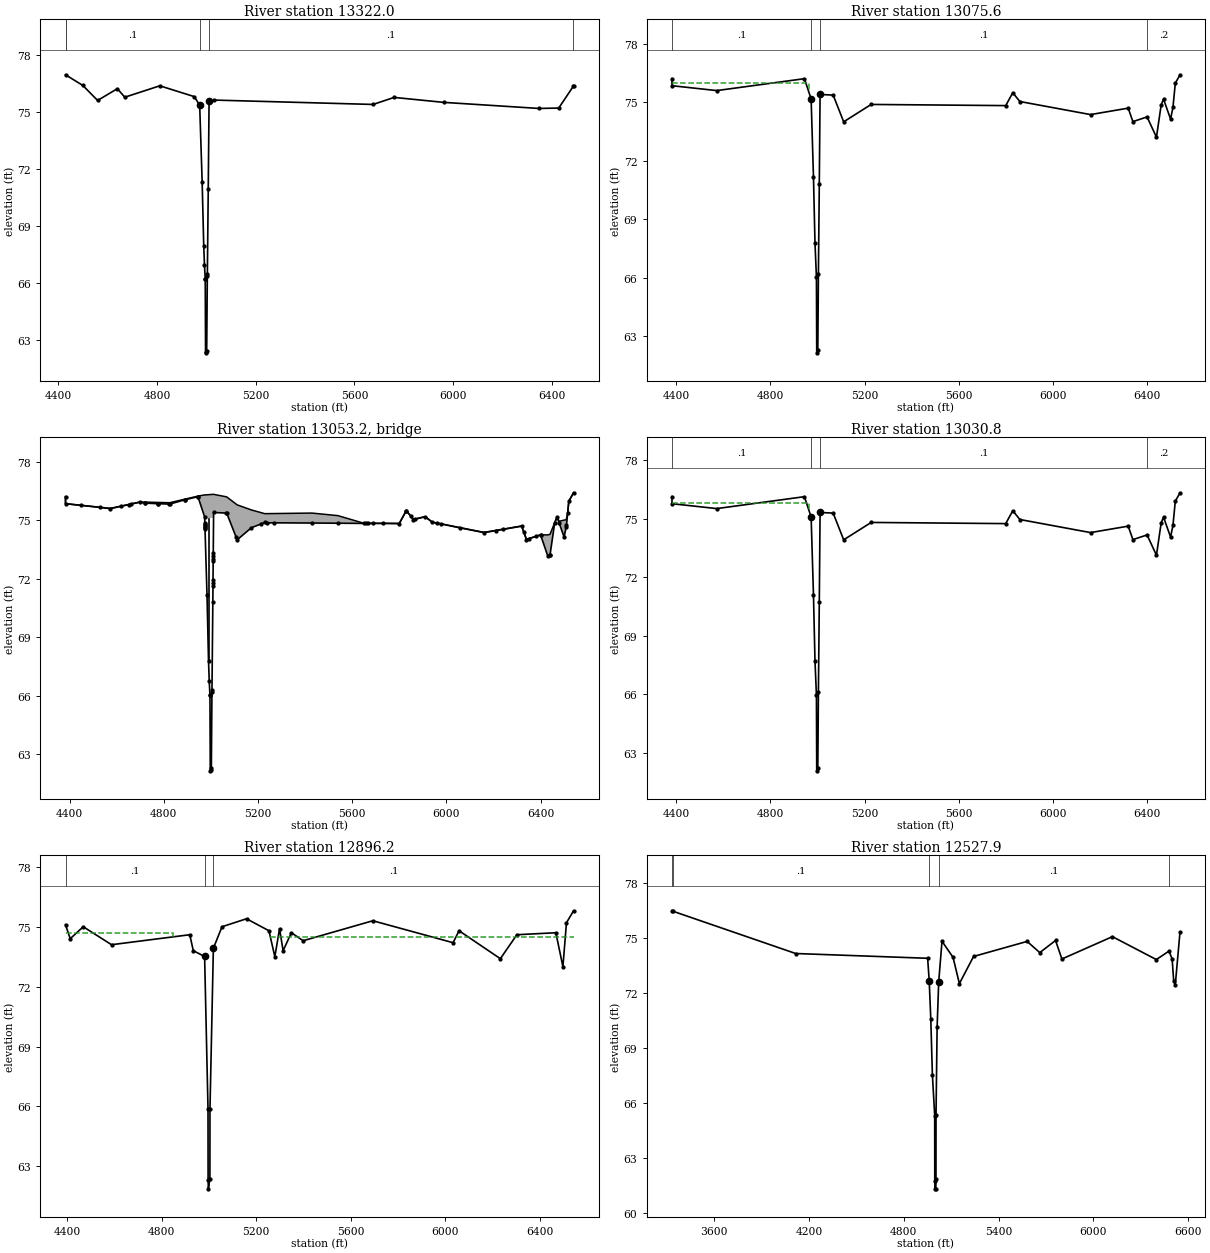
Type RM Length L Ch R = 1 ,13322.0 ,250.4,246.4,240.2
BEGIN DESCRIPTION:
Cross Section 13322.0-Interpolated
END DESCRIPTION:
XS GIS Cut Line= 6
      3071798.49     13851336.05      3071784.61     13850954.39
      3071791.55     13850610.89      3071794.44     13850025.67
      3071795.57     13849419.11      3071760.03      13849283.7
#Sta/Elev= 28
  4429.9   76.97  4499.9   76.41  4559.9   75.62  4639.9   76.24  4669.9   75.79
  4811.8   76.39  4951.8   75.82 4973.26   75.36 4983.26   71.34 4989.66   67.98
 4992.66   66.96 4995.66   66.25 4995.76   66.23 4997.06   62.35 4999.56   62.39
 5001.66   62.47 5004.16   66.37 5004.36   66.51 5007.96   70.99 5011.26   75.59
  5031.8   75.64  5675.4   75.41  5760.6   75.78  5960.6   75.52  6347.2    75.2
  6427.2   75.22    6486   76.36  6487.2   76.38
#Mann= 5 , 1 , 0
  4429.9      .2       0  4429.9      .1       0 4973.26     .04       0
 5011.26      .1       0    6486      .2       0
Bank Sta=4973.26,5011.26
XS Rating Curve= 0
Exp/Cntr=.5,.3

Type RM Length L Ch R = 1 ,13075.6 ,44.8,44.8,44.8
BEGIN DESCRIPTION:
Upstream Section of Bridge/Culvert/Weir
END DESCRIPTION:
XS GIS Cut Line= 6
      3072023.33     13851391.89      3072034.81     13850852.53
      3072048.49     13850743.16      3072128.39     13850520.56
      3072137.47     13850060.95      3072141.11     13849249.92
#Sta/Elev= 30
  4382.5    76.2  4382.6   75.84  4572.6   75.59  4944.8    76.2  4973.3   75.16
  4983.3   71.14  4989.7   67.78  4995.8   66.03  4997.1   62.15  5001.7   62.27
  5004.2   66.17    5008   70.79  5011.3   75.39  5066.8   75.36  5111.5   73.99
  5228.3   74.88  5799.5   74.82  5829.5   75.48  5859.5   75.03  6159.5   74.36
  6319.5   74.69  6339.5      74  6399.6   74.24  6439.5    73.2  6459.5   74.86
  6469.5   75.15  6499.5   74.13  6509.5   74.73  6519.5   75.97  6539.5    76.4
#Mann= 4 , 1 , 0
  4382.5      .1       0  4973.3     .04       0  5011.3      .1       0
  6399.6      .2       0
#XS Ineff= 2 , 0
       0    4964      76    5020       0    74.8
Permanent Ineff=
       F       F
Bank Sta=4973.3,5011.3
XS Rating Curve= 0
Exp/Cntr=.5,.3

Type RM Length L Ch R = 3 ,13053.2 ,,,
BEGIN DESCRIPTION:
ADKINS ROAD
Structure ID: W41-10
END DESCRIPTION:
Bridge Culvert--1,0,-1,-1, 0
Deck Dist Width WeirC Skew NumUp NumDn MinLoCord MaxHiCord MaxSubmerge Is_Ogee
10,24.8,2.6,0, 39, 39, , , .95, 0, 1,1,,
  4382.5  4382.6  4572.6  4699.3  4824.9  4944.8  4973.3 4974.61  4974.7 5009.59
  5009.7  5011.3  5066.8  5111.5  5171.9  5228.3  5428.7  5538.7  5648.7  5799.5
  5829.5  5859.5  5909.5  5939.5  6159.5  6319.5  6339.5  6399.6  6429.5  6439.5
  6459.5  6469.5  6478.4  6499.5  6508.4  6509.5  6514.4  6519.5  6539.5
    76.2   75.84    75.6   75.93   75.89   76.23   76.29   76.29   76.29   76.32
   76.32   76.32   76.19   75.78   75.52   75.33   75.36   75.23   74.84   74.83
   75.49   75.04   75.18    74.9   74.37    74.7   74.01   74.25   74.24   74.27
   74.87   75.16   74.94      75   75.02   75.08   75.35   75.97    76.4
    76.2   75.84   75.59   75.92   75.82    76.2   75.16   74.63   75.09   75.12
   73.16   75.39   75.36   73.99   74.61   74.88   74.85   74.84   74.83   74.82
   75.48   75.03   75.17   74.89   74.36   74.69      74   74.24   73.18    73.2
   74.86   75.15   74.85   74.13   74.66   74.73   75.34   75.97    76.4
  4382.5  4382.6  4572.6  4699.3  4824.9  4944.8  4973.3 4974.61  4974.7 5009.59
  5009.7  5011.3  5066.8  5111.5  5171.9  5228.3  5428.7  5538.7  5648.7  5799.5
  5829.5  5859.5  5909.5  5939.5  6159.5  6319.5  6339.5  6399.6  6429.5  6439.5
  6459.5  6469.5  6478.4  6499.5  6508.4  6509.5  6514.4  6519.5  6539.5
    76.2   75.84    75.6   75.93   75.89   76.23   76.29   76.29   76.29   76.32
   76.32   76.32   76.19   75.78   75.52   75.33   75.36   75.23   74.84   74.83
   75.49   75.04   75.18    74.9   74.37    74.7   74.01   74.25   74.24   74.27
   74.87   75.16   74.94      75   75.02   75.08   75.35   75.97    76.4
   76.15   75.79   75.54   75.87   75.77   76.15   75.11   74.58   75.04   75.07
   73.11   75.34   75.31   73.94   74.56   74.83    74.8   74.79   74.78   74.77
   75.43   74.98   75.12   74.84   74.31   74.64   73.95   74.19   73.13   73.15
   74.81    75.1    74.8   74.08   74.61   74.68   75.29   75.92   76.35
Pier Skew, UpSta & Num, DnSta & Num=  ,4989.7, 2 ,4989.7, 2 , 0 , 0 , 0 ,,
       1       1
   66.61    76.1
       1       1
   66.56   76.05
BR Coef= 1 , 1 , 0 ,1.25, 0 ,,,.8,0,2,0,
WSPro=,,,, 1 ,,,, 0 ,,,, 0 ,,,,-1 ,-1 ,-1 , 0 , 0 , 0 , 0 , 0
BR U #Sta/Elev= 95
  4382.5    76.2  4382.6   75.84    4447   75.76    4530   75.65  4572.6   75.59
    4620   75.71    4650   75.79    4660   75.82  4699.3   75.92    4719   75.87
  4720.4   75.87  4775.6   75.84  4775.8   75.84  4823.9   75.82  4824.9   75.82
  4888.9   76.04  4889.1   76.04  4944.8    76.2  4945.8   76.16  4973.3   75.16
 4974.09   74.84  4974.2    74.8 4974.31   74.75  4974.5   74.68 4974.61   74.63
  4974.7    74.6  4974.8   74.56  4983.3   71.14  4989.7   67.78  4992.7   66.76
  4995.7   66.05  4995.8   66.03  4997.1   62.15  4999.6   62.19  5001.7   62.27
  5004.2   66.17  5004.4   66.31    5008   70.79 5008.59   71.61  5008.7   71.77
 5008.81   71.92  5009.5   72.88 5009.59   73.01  5009.7   73.16  5009.8    73.3
  5011.3   75.39  5063.3   75.36  5066.8   75.36  5106.8   74.13  5111.5   73.99
  5171.9   74.61  5212.2    74.8  5228.3   74.88  5238.1   74.86  5268.7   74.86
  5428.7   74.85  5538.7   74.84  5648.7   74.83  5658.7   74.83  5668.7   74.83
  5688.7   74.83  5728.4   74.83  5799.5   74.82  5828.4   75.46  5829.5   75.48
  5848.4    75.2  5859.5   75.03  5868.4   75.05  5909.5   75.17  5939.5   74.89
  5958.4   74.84  5978.4    74.8  6058.4    74.6  6159.5   74.36  6208.4   74.46
  6238.4   74.52  6319.5   74.69  6328.4   74.38  6339.5      74  6348.4   74.04
  6378.4   74.16  6399.5   74.24  6399.6   74.24  6429.5   73.18  6438.4    73.2
  6439.5    73.2  6459.5   74.86  6469.5   75.15  6478.4   74.85  6499.5   74.13
  6508.4   74.66  6509.5   74.73  6514.4   75.34  6519.5   75.97  6539.5    76.4
BR U #Mann= 4
  4382.5      .1  4973.3     .04  5011.3      .1  6399.6      .2
BR U Banks=4973.3,5011.3
BR D #Sta/Elev= 95
  4382.5   76.15  4382.6   75.79    4447   75.71    4530    75.6  4572.6   75.54
    4620   75.66    4650   75.74    4660   75.77  4699.3   75.87    4719   75.82
  4720.4   75.82  4775.6   75.79  4775.8   75.79  4823.9   75.77  4824.9   75.77
  4888.9   75.99  4889.1   75.99  4944.8   76.15  4945.8   76.11  4973.3   75.11
 4974.09   74.79  4974.2   74.75 4974.31    74.7  4974.5   74.63 4974.61   74.58
  4974.7   74.55  4974.8   74.51  4983.3   71.09  4989.7   67.73  4992.7   66.71
  4995.7      66  4995.8   65.98  4997.1    62.1  4999.6   62.14  5001.7   62.22
  5004.2   66.12  5004.4   66.26    5008   70.74 5008.59   71.56  5008.7   71.72
 5008.81   71.87  5009.5   72.83 5009.59   72.96  5009.7   73.11  5009.8   73.25
  5011.3   75.34  5063.3   75.31  5066.8   75.31  5106.8   74.08  5111.5   73.94
  5171.9   74.56  5212.2   74.75  5228.3   74.83  5238.1   74.81  5268.7   74.81
  5428.7    74.8  5538.7   74.79  5648.7   74.78  5658.7   74.78  5668.7   74.78
  5688.7   74.78  5728.4   74.78  5799.5   74.77  5828.4   75.41  5829.5   75.43
  5848.4   75.15  5859.5   74.98  5868.4      75  5909.5   75.12  5939.5   74.84
  5958.4   74.79  5978.4   74.75  6058.4   74.55  6159.5   74.31  6208.4   74.41
  6238.4   74.47  6319.5   74.64  6328.4   74.33  6339.5   73.95  6348.4   73.99
  6378.4   74.11  6399.5   74.19  6399.6   74.19  6429.5   73.13  6438.4   73.15
  6439.5   73.15  6459.5   74.81  6469.5    75.1  6478.4    74.8  6499.5   74.08
  6508.4   74.61  6509.5   74.68  6514.4   75.29  6519.5   75.92  6539.5   76.35
BR D #Mann= 4
  4382.5      .1  4973.3     .04  5011.3      .1  6399.6      .2
BR D Banks=4973.3,5011.3
BC Design=,, 0 ,, 0 ,,,,,,
BC HTab HWMax=76.4

Type RM Length L Ch R = 1 ,13030.8 ,134.6,134.6,134.6
BEGIN DESCRIPTION:
Downstream Section of Bridge/Culvert/Weir
END DESCRIPTION:
XS GIS Cut Line= 6
      3072068.11     13851393.24      3072079.59     13850853.87
      3072093.27      13850744.5      3072173.17      13850521.9
      3072182.25     13850062.29      3072185.89     13849251.26
#Sta/Elev= 30
  4382.5   76.13  4382.6   75.77  4572.6   75.52  4944.8   76.13  4973.3   75.09
  4983.3   71.07  4989.7   67.71  4995.8   65.96  4997.1   62.08  5001.7    62.2
  5004.2    66.1    5008   70.72  5011.3   75.32  5066.8   75.29  5111.5   73.92
  5228.3   74.81  5799.5   74.75  5829.5   75.41  5859.5   74.96  6159.5   74.29
  6319.5   74.62  6339.5   73.93  6399.6   74.17  6439.5   73.13  6459.5   74.79
  6469.5   75.08  6499.5   74.06  6509.5   74.66  6519.5    75.9  6539.5   76.33
#Mann= 4 , 1 , 0
  4382.5      .1       0  4973.3     .04       0  5011.3      .1       0
  6399.6      .2       0
#XS Ineff= 2 , 0
       0    4964    75.8    5020       0    74.7
Permanent Ineff=
       F       F
Bank Sta=4973.3,5011.3
XS Rating Curve= 0
Exp/Cntr=.5,.3

Type RM Length L Ch R = 1 ,12896.2 ,369.8,368.3,367
BEGIN DESCRIPTION:
Cross Section 12896.2-Interpolated
END DESCRIPTION:
XS GIS Cut Line= 5
      3072176.07     13851387.38      3072204.72      13850897.1
      3072213.65     13850780.89      3072227.95     13850622.76
      3072228.26      13849237.7
#Sta/Elev= 30
  4392.3    75.1  4412.3    74.4  4467.3      75  4587.3    74.1  4918.5    74.6
  4933.5    73.8  4981.4   73.51  4995.8   65.86  4996.2    62.3  4997.4   61.87
  5003.8   62.38  5004.1   65.87  5018.5   73.92    5055      75  5158.8    75.4
  5253.8    74.8  5278.8    73.5  5298.8    74.9  5313.8    73.8  5348.8    74.7
  5398.8    74.3  5693.8    75.3  6033.8    74.2  6058.8    74.8  6233.8    73.4
  6303.8    74.6  6468.8    74.7  6498.8      73  6513.8    75.2  6543.8    75.8
#Mann= 3 , 1 , 0
  4392.3      .1       0  4981.4     .04       0  5018.5      .1       0
#XS Ineff= 2 , 0
       0  4847.3    74.7  5259.6       0    74.5
Permanent Ineff=
       F       F
Bank Sta=4981.4,5018.5
XS Rating Curve= 0
Exp/Cntr=.3,.1

Type RM Length L Ch R = 1 ,12527.9 ,462.4,462.6,470.5
BEGIN DESCRIPTION:
Cross Section 12527.9-Interpolated
END DESCRIPTION:
XS GIS Cut Line= 6
      3071903.23     13852237.17      3072421.35     13851649.54
      3072569.06     13851339.86      3072591.77     13850227.77
       3072612.1     13849400.01      3072538.41     13849269.34
#Sta/Elev= 30
  3332.2   76.46  3336.5   76.44  4115.6   74.13  4951.1   73.87  4961.1   72.63
  4971.1   70.55  4981.1   67.53  4995.8   65.29  4996.2   61.73  4997.4    61.3
  5002.9    61.3  5003.8   61.81  5004.1    65.3  5011.1   70.12  5021.1   72.58
    5042    74.8    5112   73.92    5152   72.49    5242   73.97  5581.1   74.79
  5661.1   74.18  5761.1   74.84  5801.1   73.83  6121.1   75.05  6399.1    73.8
  6479.2   74.26  6499.1   73.84  6509.1   72.63  6519.1   72.42  6549.1   75.31
#Mann= 5 , 1 , 0
  3332.2      .2       0  3336.5      .1       0  4961.1     .04       0
  5021.1      .1       0  6479.2      .2       0
#XS Ineff= 2 , 0
       0                  5081.3       0    74.3
Permanent Ineff=
       F       F
Bank Sta=4961.1,5021.1
XS Rating Curve= 0
Exp/Cntr=.3,.1

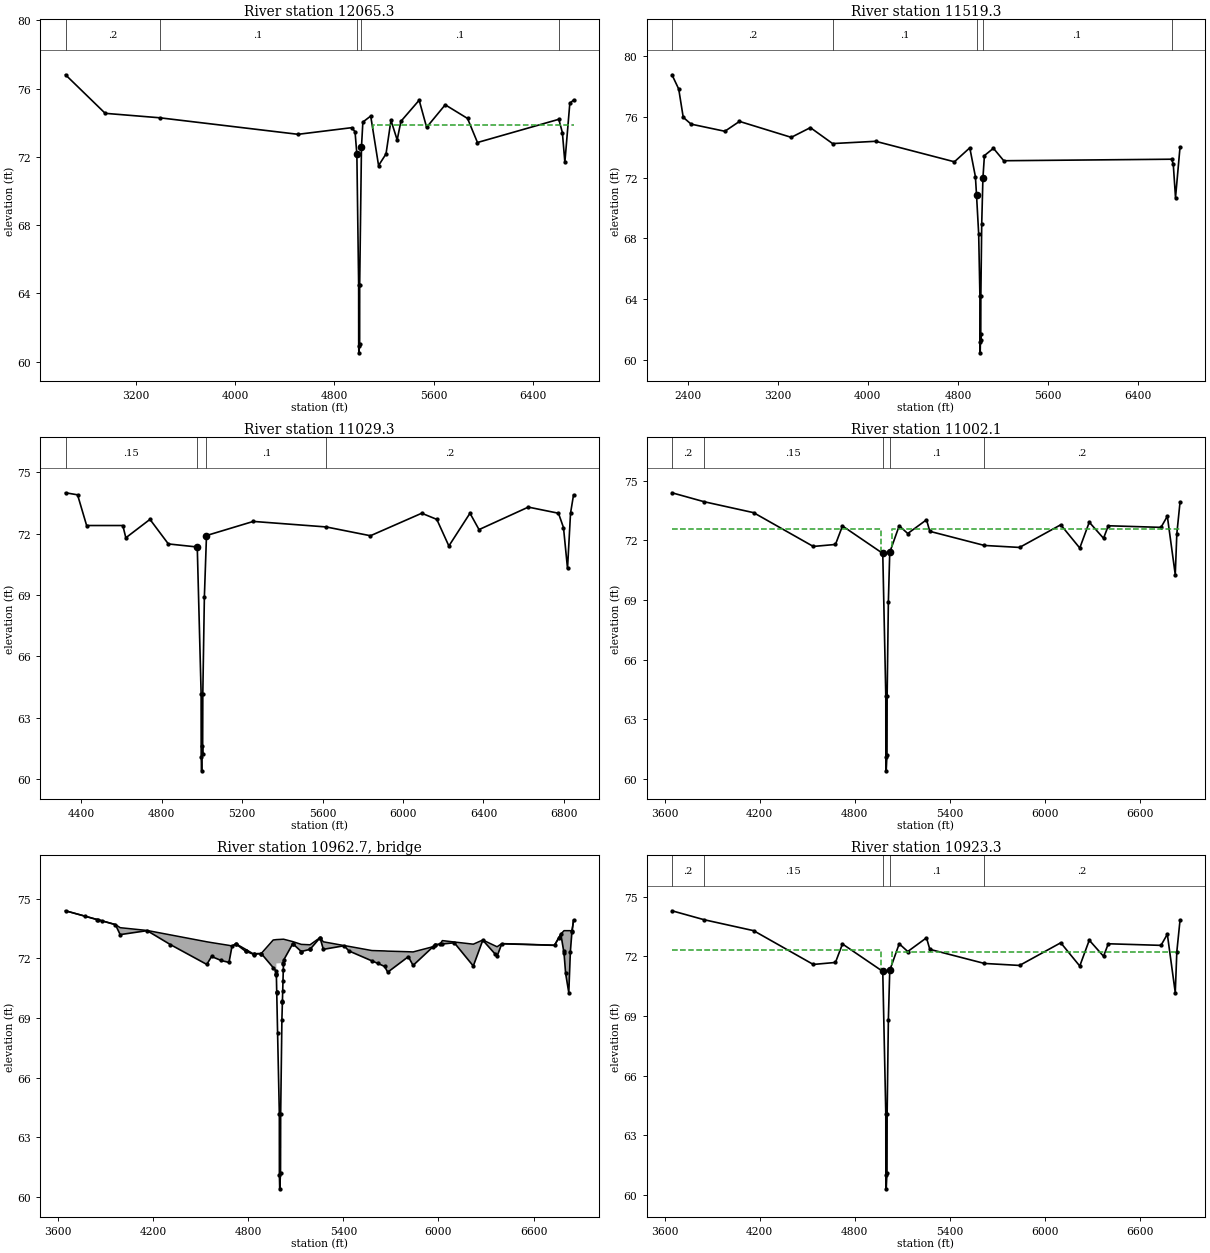
Type RM Length L Ch R = 1 ,12065.3 ,483.5,546,557.5
BEGIN DESCRIPTION:
Cross Section 12065.3
END DESCRIPTION:
XS GIS Cut Line= 6
      3071916.22     13852769.33      3072724.81     13852009.92
      3073023.47     13851348.77      3073072.47     13850373.64
       3073084.8      13849659.2      3072688.01     13849249.88
#Sta/Elev= 30
  2632.5   76.81  2952.5   74.55  3390.6   74.29  4507.3   73.32  4940.5   73.71
  4966.8   73.47  4981.4   72.15  4995.8    64.5  4996.2   60.94  4997.4   60.51
  5003.8   61.02  5004.1   64.51  5018.5   72.56  5029.8   74.04  5093.1   74.39
  5156.4   71.49  5216.4   72.17  5256.4   74.14  5306.4   72.99  5336.4   74.08
  5483.7   75.32  5543.7   73.73  5693.7   75.05  5873.7   74.25  5953.7   72.84
  6609.5    74.2  6638.3   73.42  6658.3   71.68  6698.3   75.14  6728.3   75.33
#Mann= 5 , 1 , 0
  2632.5      .2       0  3390.6      .1       0  4981.4     .04       0
  5018.5      .1       0  6609.5     .99       0
#XS Ineff= 2 , 0
       0                  5109.4       0   73.85
Permanent Ineff=
       F       F
Bank Sta=4981.4,5018.5
XS Rating Curve= 0
Exp/Cntr=.3,.1

Type RM Length L Ch R = 1 ,11519.3 ,553.7,490,416.2
BEGIN DESCRIPTION:
Cross Section 11519.3-Interpolated
END DESCRIPTION:
XS GIS Cut Line= 6
      3072240.49      13853456.7      3072871.31     13852604.71
      3073487.71     13851142.67      3073570.14      13850936.6
      3073598.93     13850000.67      3073626.48     13849291.15
#Sta/Elev= 30
  2259.1   78.77  2319.1   77.83  2359.1   75.97  2429.1   75.52  2729.1   75.05
  2859.1    75.7  3319.2   74.65  3489.2   75.29  3686.6   74.24  4069.2   74.39
  4769.2   73.04  4905.9   73.96  4955.9   72.06  4965.9   70.83  4984.8    68.3
  4995.8   64.23  4996.1   61.16  4998.3   60.46  5001.7   61.67  5003.3   61.28
  5004.2   64.22    5012   68.97  5022.5   71.96  5035.9   73.45  5115.9   73.93
  5207.8   73.11  6699.1   73.21  6714.2   72.89  6734.2   70.68  6774.2      74
#Mann= 5 , 1 , 0
  2259.1      .2       0  3686.6      .1       0  4965.9     .04       0
  5022.5      .1       0  6699.1      .2       0
#XS Ineff= 2 , 0
       0                  6323.2       0      73
Permanent Ineff=
       F       F
Bank Sta=4965.9,5022.5
XS Rating Curve= 0
Exp/Cntr=.3,.1

Type RM Length L Ch R = 1 ,11029.3 ,26.7,27.2,48.2
BEGIN DESCRIPTION:
Cross Section 11029.3-Interpolated
END DESCRIPTION:
XS GIS Cut Line= 6
       3073972.2     13851819.13      3073997.93     13851363.46
      3074002.93     13851141.02      3073999.54     13850846.79
      3073998.31     13850608.56      3073894.76     13849297.62
#Sta/Elev= 30
  4321.4      74  4381.4    73.9  4426.4    72.4  4606.4    72.4  4621.4    71.8
  4741.4    72.7  4832.8    71.5  4976.6   71.35  4995.8   64.18  4996.1   61.11
  4998.3   60.41  5001.7   61.62  5003.3   61.23  5004.2   64.17    5012   68.92
  5022.5   71.91  5255.3    72.6    5618   72.33  5837.8    71.9  6092.8      73
  6167.8    72.7  6227.8    71.4  6332.8      73  6377.8    72.2  6622.8    73.3
  6772.8      73  6797.8    72.3  6817.8    70.3  6832.8      73  6847.8    73.9
#Mann= 4 , 1 , 0
  4321.4     .15       0  4976.6    .025       0  5022.5      .1       0
    5618      .2       0
#XS Ineff= 2 , 0
       0  4741.4    72.7  5255.3       0    72.6
Permanent Ineff=
       F       F
Bank Sta=4976.6,5022.5
XS Rating Curve= 0
Exp/Cntr=.5,.3

Type RM Length L Ch R = 1 ,11002.1 ,78.8,78.8,78.8
BEGIN DESCRIPTION:
Upstream Section of Bridge/Culvert/Weir
END DESCRIPTION:
XS GIS Cut Line= 6
      3074004.18     13852498.19      3074020.78     13851809.56
      3074027.62     13851344.71      3074027.62     13851194.32
      3074048.12      13850565.4      3073939.91     13849297.09
#Sta/Elev= 30
  3646.3    74.4    3849   73.95  4161.3    73.4  4538.1    71.7  4678.1    71.8
  4722.3   72.73  4976.6   71.35  4995.8   64.18  4996.1   61.11  4998.3   60.41
  5003.3   61.23  5004.2   64.17    5012   68.92  5020.7    71.4  5080.4   72.74
  5134.3   72.35  5252.6   73.04  5273.6   72.46    5618   71.75  5839.9   71.65
  6099.9   72.79  6219.9   71.62  6279.9   72.92  6369.9   72.11  6399.9   72.74
  6732.6   72.66  6772.6   73.22  6822.6   70.28  6832.6   72.35  6852.6   73.92
#Mann= 5 , 1 , 0
  3646.3      .2       0    3849     .15       0  4976.6    .035       0
  5020.7      .1       0    5618      .2       0
#XS Ineff= 2 , 0
       0    4967    72.6    5032       0    72.6
Permanent Ineff=
       F       F
Bank Sta=4976.6,5020.7
XS Rating Curve= 0
Exp/Cntr=.5,.3

Type RM Length L Ch R = 3 ,10962.7 ,,,
BEGIN DESCRIPTION:
CAMPBELL ROAD
Structure ID: W41-9
END DESCRIPTION:
Bridge Culvert--1,0,-1,-1, 0
Deck Dist Width WeirC Skew NumUp NumDn MinLoCord MaxHiCord MaxSubmerge Is_Ogee
10,58.8,2.6,0, 47, 47, , , .95, 0, 1,1,,
  3646.3  3961.3  3991.3  4161.3  4538.1  4568.1  4678.1  4697.1  4722.3  4783.4
  4836.7  4881.4    4957  4976.6 4976.91    4977    5022  5022.5  5080.4  5134.3
  5189.7  5252.6  5273.6  5404.6  5434.6  5579.7  5659.9  5679.9  5809.9  5839.9
  5964.7  5979.7  6009.7  6024.7  6099.9  6219.9  6279.9  6369.9  6399.9  6732.6
  6772.6  6792.6  6802.6  6822.6  6832.6  6842.6  6852.6
    74.4   73.71   73.55   73.41   72.84    72.8   72.66   72.63   72.74   72.46
   72.21   72.25   72.93   72.95   72.95   72.95   72.97   72.97   72.85   72.71
   72.69   73.05   72.84   72.65   72.61    72.4   72.38   72.37   72.34   72.33
   72.59    72.7   72.72    72.9   72.83   72.72   72.93   72.59   72.75   72.67
   73.23    73.4    73.4    73.4    73.4   73.36   73.92
    74.4    73.7    73.2    73.4    71.7    72.1    71.8   72.61   72.73   72.36
    72.2   72.25   71.54   71.35   71.23   71.75   71.77   71.91   72.74   72.35
   72.46   73.04   72.46   72.64   72.38   71.88    71.6   71.31   72.09   71.65
   72.58   72.69   72.71   72.73   72.79   71.62   72.92   72.11   72.74   72.66
   73.22   72.26   71.25   70.28   72.35   73.36   73.92
  3646.3  3961.3  3991.3  4161.3  4538.1  4568.1  4678.1  4697.1  4722.3  4783.4
  4836.7  4881.4    4957  4976.6 4976.91    4977    5022  5022.5  5080.4  5134.3
  5189.7  5252.6  5273.6  5404.6  5434.6  5579.7  5659.9  5679.9  5809.9  5839.9
  5964.7  5979.7  6009.7  6024.7  6099.9  6219.9  6279.9  6369.9  6399.9  6732.6
  6772.6  6792.6  6802.6  6822.6  6832.6  6842.6  6852.6
    74.4   73.71   73.55   73.41   72.84    72.8   72.66   72.63   72.74   72.46
   72.21   72.25   72.93   72.95   72.95   72.95   72.97   72.97   72.85   72.71
   72.69   73.05   72.84   72.65   72.61    72.4   72.38   72.37   72.34   72.33
   72.59    72.7   72.72    72.9   72.83   72.72   72.93   72.59   72.75   72.67
   73.23    73.4    73.4    73.4    73.4   73.36   73.92
   74.31   73.61   73.11   73.31   71.61   72.01   71.71   72.52   72.64   72.27
   72.11   72.16   71.45   71.26   71.14   71.66   71.68   71.82   72.65   72.26
   72.37   72.95   72.37   72.55   72.29   71.79   71.51   71.22      72   71.56
   72.49    72.6   72.62   72.64    72.7   71.53   72.83   72.02   72.65   72.57
   73.13   72.17   71.16   70.19   72.26   73.27   73.83
Abutment Skew #Up #Dn= , 2 , 2
  5018.9 5022.09
   70.89   71.77
  5018.9 5022.09
    70.8   71.68
BR Coef= 1 , 1 , 0 ,1.25, 0 ,,,.8,-1,2,0,
WSPro=,,,, 1 ,,,, 0 ,,,, 0 ,,,,-1 ,-1 ,-1 , 0 , 0 , 0 , 0 , 0
BR U #Sta/Elev= 86
  3646.3    74.4  3767.6   74.13  3847.6   73.95    3849   73.95  3877.6   73.89
  3961.3    73.7  3991.3    73.2  4161.3    73.4  4308.1    72.7  4538.1    71.7
  4568.1    72.1  4628.1    71.9  4678.1    71.8  4697.1   72.61  4722.3   72.73
  4723.7   72.72  4783.4   72.36  4784.1   72.36  4836.7    72.2  4837.5   72.22
  4838.3   72.24  4881.1   72.25  4881.4   72.25    4957   71.54  4976.6   71.35
 4976.91   71.23    4977    71.2  4977.1   71.16 4979.29   70.33  4979.4   70.29
 4979.51   70.25  4984.8   68.25  4995.8   64.18  4996.1   61.11  4998.3   60.41
  5003.3   61.23  5004.2   64.17    5012   68.92 5015.09    69.8  5015.2   69.83
 5015.31   69.86  5017.1   70.37  5018.9   70.89  5020.7    71.4 5021.89   71.74
    5022   71.77  5022.5   71.91  5080.4   72.74  5082.3   72.73  5134.2   72.35
  5134.3   72.35  5189.4   72.46  5189.7   72.46  5252.6   73.04  5253.4   73.02
  5273.6   72.46  5404.6   72.64  5434.6   72.38  5579.7   71.88    5618   71.75
  5659.9    71.6  5679.9   71.31  5809.9   72.09  5839.9   71.65  5964.7   72.58
  5979.7   72.69  5979.9   72.69  6009.7   72.71  6024.7   72.73  6099.9   72.79
  6219.9   71.62  6279.9   72.92  6354.7   72.25  6369.9   72.11  6399.9   72.74
  6732.6   72.66  6759.7   73.04  6772.6   73.22  6789.7    72.4  6792.6   72.26
  6802.6   71.25  6822.6   70.28  6832.6   72.35  6842.5   73.35  6842.6   73.36
  6852.6   73.92
BR U #Mann= 5
  3646.3      .2    3849     .15  4976.6    .035  5020.7      .1    5618      .2
BR U Banks=4976.6,5020.7
BR D #Sta/Elev= 86
  3646.3   74.31  3767.6   74.04  3847.6   73.86    3849   73.86  3877.6    73.8
  3961.3   73.61  3991.3   73.11  4161.3   73.31  4308.1   72.61  4538.1   71.61
  4568.1   72.01  4628.1   71.81  4678.1   71.71  4697.1   72.52  4722.3   72.64
  4723.7   72.63  4783.4   72.27  4784.1   72.27  4836.7   72.11  4837.5   72.13
  4838.3   72.15  4881.1   72.16  4881.4   72.16    4957   71.45  4976.6   71.26
 4976.91   71.14    4977   71.11  4977.1   71.07 4979.29   70.24  4979.4    70.2
 4979.51   70.16  4984.8   68.16  4995.8   64.09  4996.1   61.02  4998.3   60.32
  5003.3   61.14  5004.2   64.08    5012   68.83 5015.09   69.71  5015.2   69.74
 5015.31   69.77  5017.1   70.28  5018.9    70.8  5020.7   71.31 5021.89   71.65
    5022   71.68  5022.5   71.82  5080.4   72.65  5082.3   72.64  5134.2   72.26
  5134.3   72.26  5189.4   72.37  5189.7   72.37  5252.6   72.95  5253.4   72.93
  5273.6   72.37  5404.6   72.55  5434.6   72.29  5579.7   71.79    5618   71.66
  5659.9   71.51  5679.9   71.22  5809.9      72  5839.9   71.56  5964.7   72.49
  5979.7    72.6  5979.9    72.6  6009.7   72.62  6024.7   72.64  6099.9    72.7
  6219.9   71.53  6279.9   72.83  6354.7   72.16  6369.9   72.02  6399.9   72.65
  6732.6   72.57  6759.7   72.95  6772.6   73.13  6789.7   72.31  6792.6   72.17
  6802.6   71.16  6822.6   70.19  6832.6   72.26  6842.5   73.26  6842.6   73.27
  6852.6   73.83
BR D #Mann= 5
  3646.3      .2    3849     .15  4976.6    .035  5020.7      .1    5618      .2
BR D Banks=4976.6,5020.7
BC Design=,, 0 ,, 0 ,,,,,,
BC HTab HWMax=74.4

Type RM Length L Ch R = 1 ,10923.3 ,158.5,158.5,158.5
BEGIN DESCRIPTION:
Downstream Section of Bridge/Culvert/Weir
END DESCRIPTION:
XS GIS Cut Line= 6
      3074082.97     13852499.56      3074099.56     13851810.94
       3074106.4     13851346.09       3074106.4      13851195.7
       3074126.9     13850566.78       3074018.7     13849298.46
#Sta/Elev= 30
  3646.3   74.29    3849   73.84  4161.3   73.29  4538.1   71.59  4678.1   71.69
  4722.3   72.62  4976.6   71.24  4995.8   64.07  4996.1      61  4998.3    60.3
  5003.3   61.12  5004.2   64.06    5012   68.81  5020.7   71.29  5080.4   72.63
  5134.3   72.24  5252.6   72.93  5273.6   72.35    5618   71.64  5839.9   71.54
  6099.9   72.68  6219.9   71.51  6279.9   72.81  6369.9      72  6399.9   72.63
  6732.6   72.55  6772.6   73.11  6822.6   70.17  6832.6   72.24  6852.6   73.81
#Mann= 5 , 1 , 0
  3646.3      .2       0    3849     .15       0  4976.6    .035       0
  5020.7      .1       0    5618      .2       0
#XS Ineff= 2 , 0
       0    4967    72.3    5032       0    72.2
Permanent Ineff=
       F       F
Bank Sta=4976.6,5020.7
XS Rating Curve= 0
Exp/Cntr=.5,.3