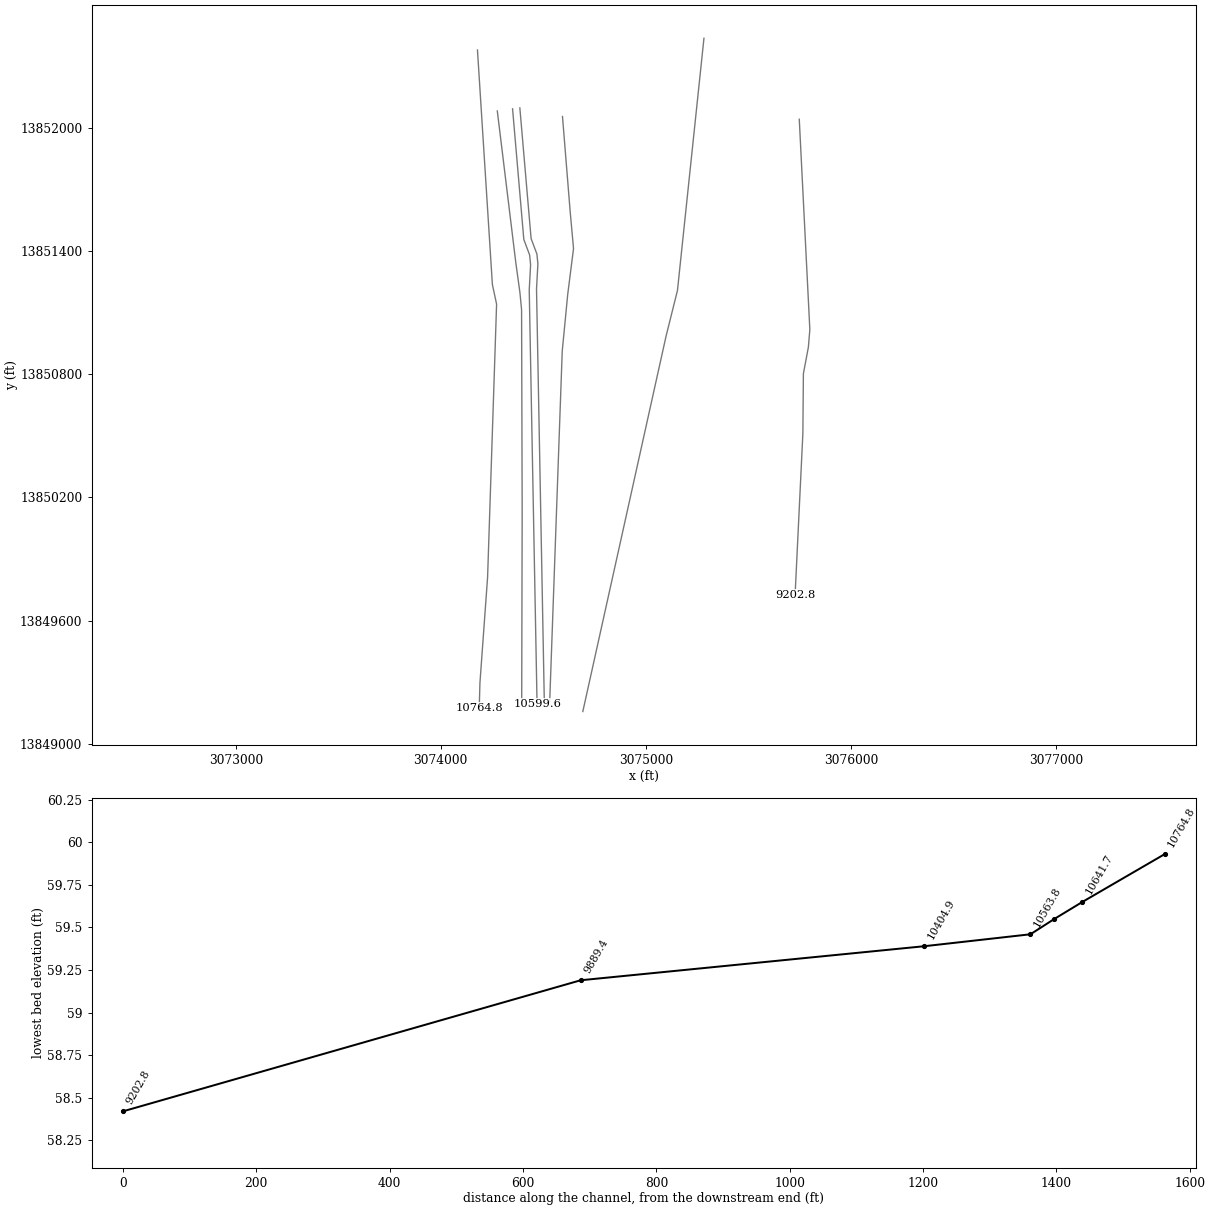
HEC-RAS study W140-01-00.PRJ: W140-01-00

--- W140-01-00.g01 (geometry) --- (continued)

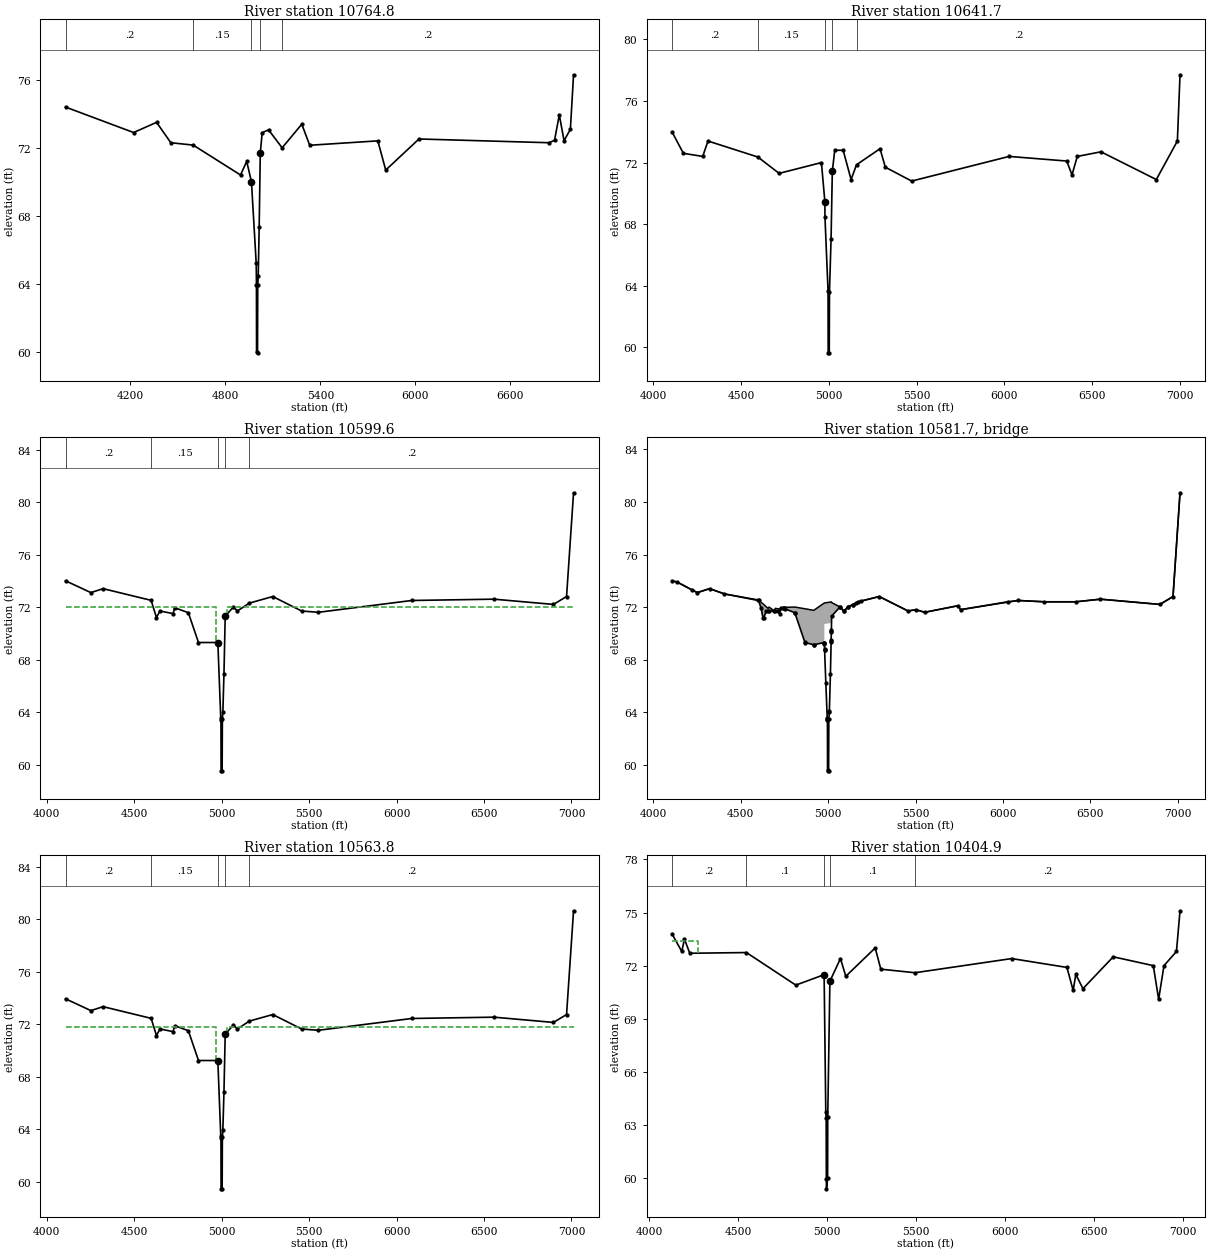
Type RM Length L Ch R = 1 ,10764.8 ,122.2,123.1,143.5
BEGIN DESCRIPTION:
Cross Section 10764.8-Interpolated
END DESCRIPTION:
XS GIS Cut Line= 6
      3074178.76     13852377.76      3074251.58     13851236.02
      3074272.09     13851140.32      3074228.21     13849811.39
      3074190.84      13849296.5      3074187.52     13849176.54
#Sta/Elev= 30
  3790.4    74.4  4220.4    72.9  4365.4    73.5  4455.4    72.3  4596.8   72.16
  4895.4    70.4  4934.5    71.2  4964.5      70  4994.5    65.2    4996   63.95
  4996.7   59.95  5002.8   59.93  5004.1   63.91  5007.2   64.44  5013.2   67.32
  5020.3   71.71  5032.3   72.89  5072.3   73.06  5158.2      72  5282.3   73.39
  5332.3   72.15  5762.3   72.41  5812.3   70.69  6022.3   72.52    6842    72.3
  6878.2   72.44  6908.2   73.94  6938.2   72.42  6978.2   73.09  6998.2    76.3
#Mann= 5 , 1 , 0
  3790.4      .2       0  4596.8     .15       0  4964.5    .025       0
  5020.3      .1       0  5158.2      .2       0
#XS Ineff= 2 , 0
       0                  5765.2       0   72.23
Permanent Ineff=
       F       F
Bank Sta=4964.5,5020.3
XS Rating Curve= 0
Exp/Cntr=.3,.1

Type RM Length L Ch R = 1 ,10641.7 ,42,42.1,46.4
BEGIN DESCRIPTION:
Cross Section 10641.7-Interpolated
END DESCRIPTION:
XS GIS Cut Line= 6
      3074275.56     13852080.85      3074366.09      13851340.4
      3074386.01     13851195.97      3074393.98      13851113.3
      3074396.88     13850125.37      3074394.52     13849195.34
#Sta/Elev= 30
  4107.3      74  4172.3    72.6  4282.3    72.4  4312.3    73.4  4596.8   72.36
  4717.3    71.3  4958.3      72  4978.2   69.42  4978.3    68.5    4996   63.67
  4996.7   59.67  5002.8   59.65  5004.1   63.63  5013.2   67.04  5020.3   71.43
  5034.1    72.8  5082.1    72.8  5127.1    70.9  5158.2   71.86  5292.1    72.9
  5322.1    71.7  5472.1    70.8  6027.1    72.4  6355.1    72.1  6385.1    71.2
  6415.1    72.4  6550.1    72.7  6865.1    70.9  6985.1    73.4  7000.1    77.7
#Mann= 5 , 1 , 0
  4107.3      .2       0  4596.8     .15       0  4978.2    .025       0
  5020.3      .1       0  5158.2      .2       0
#XS Ineff= 2 , 0
       0                  5304.6       0    72.4
Permanent Ineff=
       F       F
Bank Sta=4978.2,5020.3
XS Rating Curve= 0
Exp/Cntr=.5,.3

Type RM Length L Ch R = 1 ,10599.6 ,35.8,35.8,35.8
BEGIN DESCRIPTION:
Upstream Section of Bridge/Culvert/Weir
END DESCRIPTION:
XS GIS Cut Line= 6
      3074349.98     13852091.38      3074404.89     13851455.34
      3074433.25     13851379.71      3074437.97     13851332.45
      3074431.33     13851209.54      3074469.46     13849194.65
#Sta/Elev= 30
  4107.1   74.02  4252.1   73.12  4322.1   73.42  4596.8   72.53  4627.1   71.22
  4647.1   71.72  4722.1   71.52  4731.3   71.97  4809.5   71.59  4867.5   69.32
  4978.2   69.32  4995.2   63.45    4996   63.57  4996.7   59.57  5002.8   59.55
  5004.1   63.53    5007   64.06  5013.2   66.94  5020.3   71.33  5067.2   72.02
  5089.7   71.72  5158.2   72.32  5292.2   72.82  5457.2   71.72  5552.2   71.62
  6087.2   72.52  6557.2   72.62  6897.2   72.22  6972.2   72.82  7012.2   80.72
#Mann= 5 , 1 , 0
  4107.1      .2       0  4596.8     .15       0  4978.2    .025       0
  5020.3      .1       0  5158.2      .2       0
#XS Ineff= 2 , 0
       0    4968      72    5028       0      72
Permanent Ineff=
       F       F
Bank Sta=4978.2,5020.3
XS Rating Curve= 0
Exp/Cntr=.5,.3

Type RM Length L Ch R = 3 ,10581.7 ,,,
BEGIN DESCRIPTION:
TAMY ROAD
Structure ID: W41-8
END DESCRIPTION:
Bridge Culvert--1,0,-1,-1, 0
Deck Dist Width WeirC Skew NumUp NumDn MinLoCord MaxHiCord MaxSubmerge Is_Ogee
10,15.8,2.6,0, 45, 45, , , .95, 0, 1,1,,
  4107.1  4137.1  4252.1  4322.1  4407.1  4602.1  4617.1  4627.1  4632.1  4647.1
  4656.8  4661.8    4693    4698  4712.1  4722.1  4731.3  4748.7  4752.1  4809.5
  4867.5  4917.9  4978.2 4978.41  4978.5 5018.39  5018.5  5020.3  5067.2  5089.7
  5115.5  5172.2  5292.2  5457.2  5502.2  5552.2  5742.2  5757.2  6087.2  6237.2
  6417.2  6557.2  6897.2  6972.2  7012.2
      74    73.9    73.1    73.4      73   72.54   72.36   72.25   72.19   72.01
    71.9      72   71.71    71.9   71.87   71.85   71.96   71.89   71.98      72
   71.87   71.75   72.31   72.31   72.31   72.39   72.39   72.34   72.01   71.71
   72.02   72.41    72.8    71.7    71.8    71.6    72.1    71.8    72.5    72.4
    72.4    72.6    72.2    72.8    80.7
      74    73.9    73.1    73.4      73    72.5    71.9    71.2    71.2    71.7
    71.7    71.7    71.7    71.7    71.7    71.5   71.95   71.89   71.87   71.57
    69.3   69.13    69.3   69.23   70.71   70.79    70.2   71.31      72    71.7
   72.01    72.4    72.8    71.7    71.8    71.6    72.1    71.8    72.5    72.4
    72.4    72.6    72.2    72.8    80.7
  4107.1  4137.1  4252.1  4322.1  4407.1  4602.1  4617.1  4627.1  4632.1  4647.1
  4656.8  4661.8    4693    4698  4712.1  4722.1  4731.3  4748.7  4752.1  4809.5
  4867.5  4917.9  4978.2 4978.41  4978.5 5018.39  5018.5  5020.3  5067.2  5089.7
  5115.5  5172.2  5292.2  5457.2  5502.2  5552.2  5742.2  5757.2  6087.2  6237.2
  6417.2  6557.2  6897.2  6972.2  7012.2
      74    73.9    73.1    73.4      73   72.54   72.36   72.25   72.19   72.01
    71.9      72   71.71    71.9   71.87   71.85   71.96   71.89   71.98      72
   71.87   71.75   72.31   72.31   72.31   72.39   72.39   72.34   72.01   71.71
   72.02   72.41    72.8    71.7    71.8    71.6    72.1    71.8    72.5    72.4
    72.4    72.6    72.2    72.8    80.7
   73.93   73.83   73.03   73.33   72.93   72.43   71.83   71.13   71.13   71.63
   71.63   71.63   71.63   71.63   71.63   71.43   71.88   71.82    71.8    71.5
   69.23   69.06   69.23   69.16   70.64   70.72   70.13   71.24   71.93   71.63
   71.94   72.33   72.73   71.63   71.73   71.53   72.03   71.73   72.43   72.33
   72.33   72.53   72.13   72.73   80.63
Abutment Skew #Up #Dn= , 2 , 2
  4978.3  4995.3
   70.71   63.45
  4978.3  4995.3
   70.64   63.38
Abutment Skew #Up #Dn= , 2 , 2
  5007.2 5018.59
   64.14   70.79
  5007.2 5018.59
   64.07   70.72
BR Coef= 1 , 1 , 0 ,1.25, 0 ,,,.8,0,2,0,
WSPro=,,,, 1 ,,,, 0 ,,,, 0 ,,,,-1 ,-1 ,-1 , 0 , 0 , 0 , 0 , 0
BR U #Sta/Elev= 79
  4107.1      74  4137.1    73.9  4222.1    73.3  4252.1    73.1  4322.1    73.4
  4407.1      73  4596.8   72.51  4602.1    72.5  4617.1    71.9  4627.1    71.2
  4632.1    71.2  4647.1    71.7  4656.8    71.7  4661.8    71.7    4693    71.7
    4698    71.7  4712.1    71.7  4722.1    71.5  4731.3   71.95    4743   71.91
  4745.5    71.9  4748.7   71.89  4752.1   71.87  4809.1   71.57  4809.5   71.57
  4866.9   69.32  4867.5    69.3  4917.9   69.13  4918.1   69.13  4978.2    69.3
  4978.3   69.26 4978.41   69.23  4978.5   69.19 4979.69   68.78  4979.8   68.74
 4979.91    68.7    4987    66.2  4995.2   63.43  4995.3   63.45    4996   63.55
  4996.7   59.55  4999.8   59.57  5002.8   59.53  5004.1   63.51    5007   64.04
  5007.1   64.09  5013.2   66.92 5017.09   69.33  5017.2   69.39 5017.31   69.46
 5018.39   70.13  5018.5    70.2  5018.6   70.26  5020.3   71.31  5067.2      72
  5067.5      72  5088.8   71.71  5089.7    71.7  5115.5   72.01  5115.9   72.01
  5139.4   72.17    5142   72.19  5158.2    72.3  5172.2    72.4  5188.2   72.45
  5292.2    72.8  5457.2    71.7  5502.2    71.8  5552.2    71.6  5742.2    72.1
  5757.2    71.8  6027.2    72.4  6087.2    72.5  6237.2    72.4  6417.2    72.4
  6557.2    72.6  6897.2    72.2  6972.2    72.8  7012.2    80.7
BR U #Mann= 5
  4107.1      .2  4596.8     .15  4978.2    .025  5020.3      .1  5158.2      .2
BR U Banks=4978.2,5020.3
BR D #Sta/Elev= 79
  4107.1   73.93  4137.1   73.83  4222.1   73.23  4252.1   73.03  4322.1   73.33
  4407.1   72.93  4596.8   72.44  4602.1   72.43  4617.1   71.83  4627.1   71.13
  4632.1   71.13  4647.1   71.63  4656.8   71.63  4661.8   71.63    4693   71.63
    4698   71.63  4712.1   71.63  4722.1   71.43  4731.3   71.88    4743   71.84
  4745.5   71.83  4748.7   71.82  4752.1    71.8  4809.1    71.5  4809.5    71.5
  4866.9   69.25  4867.5   69.23  4917.9   69.06  4918.1   69.06  4978.2   69.23
  4978.3   69.19 4978.41   69.16  4978.5   69.12 4979.69   68.71  4979.8   68.67
 4979.91   68.63    4987   66.13  4995.2   63.36  4995.3   63.38    4996   63.48
  4996.7   59.48  4999.8    59.5  5002.8   59.46  5004.1   63.44    5007   63.97
  5007.1   64.02  5013.2   66.85 5017.09   69.26  5017.2   69.32 5017.31   69.39
 5018.39   70.06  5018.5   70.13  5018.6   70.19  5020.3   71.24  5067.2   71.93
  5067.5   71.93  5088.8   71.64  5089.7   71.63  5115.5   71.94  5115.9   71.94
  5139.4    72.1    5142   72.12  5158.2   72.23  5172.2   72.33  5188.2   72.38
  5292.2   72.73  5457.2   71.63  5502.2   71.73  5552.2   71.53  5742.2   72.03
  5757.2   71.73  6027.2   72.33  6087.2   72.43  6237.2   72.33  6417.2   72.33
  6557.2   72.53  6897.2   72.13  6972.2   72.73  7012.2   80.63
BR D #Mann= 5
  4107.1      .2  4596.8     .15  4978.2    .025  5020.3      .1  5158.2      .2
BR D Banks=4978.2,5020.3
BC Design=,, 0 ,, 0 ,,,,,,
BC HTab HWMax=80.72

Type RM Length L Ch R = 1 ,10563.8 ,158.9,158.9,158.9
BEGIN DESCRIPTION:
Downstream Section of Bridge/Culvert/Weir
END DESCRIPTION:
XS GIS Cut Line= 6
      3074385.51     13852095.77      3074440.43     13851459.72
      3074468.79     13851384.09      3074473.51     13851336.83
      3074466.87     13851213.92      3074504.99     13849199.04
#Sta/Elev= 30
  4107.1   73.93  4252.1   73.03  4322.1   73.33  4596.8   72.44  4627.1   71.13
  4647.1   71.63  4722.1   71.43  4731.3   71.88  4809.5    71.5  4867.5   69.23
  4978.2   69.23  4995.2   63.36    4996   63.48  4996.7   59.48  5002.8   59.46
  5004.1   63.44    5007   63.97  5013.2   66.85  5020.3   71.24  5067.2   71.93
  5089.7   71.63  5158.2   72.23  5292.2   72.73  5457.2   71.63  5552.2   71.53
  6087.2   72.43  6557.2   72.53  6897.2   72.13  6972.2   72.73  7012.2   80.63
#Mann= 5 , 1 , 0
  4107.1      .2       0  4596.8     .15       0  4978.2    .025       0
  5020.3      .1       0  5158.2      .2       0
#XS Ineff= 2 , 0
       0    4968    71.8    5028       0    71.8
Permanent Ineff=
       F       F
Bank Sta=4978.2,5020.3
XS Rating Curve= 0
Exp/Cntr=.5,.3

Type RM Length L Ch R = 1 ,10404.9 ,523.7,515.5,456.2
BEGIN DESCRIPTION:
Cross Section 10404.9-Interpolated
END DESCRIPTION:
XS GIS Cut Line= 6
      3074593.49     13852054.09      3074631.18     13851588.77
      3074647.35     13851410.97      3074618.91     13851187.06
      3074592.26     13850911.61      3074531.22      13849207.7
#Sta/Elev= 30
  4129.6    73.8  4184.6    72.8  4199.6    73.5  4229.6    72.7  4547.7   72.74
    4825    70.9  4983.9   71.49  4993.3   63.73  4995.5    63.4  4996.4   59.92
  4997.3   59.39  5003.6   59.99  5004.3   63.47  5016.4   71.12  5075.7    72.4
  5105.7    71.4  5270.7      73  5302.4    71.8  5494.7    71.6  6037.4    72.4
  6347.4    71.9  6382.4    70.6  6397.4    71.5  6437.4    70.7  6607.4    72.5
  6832.4      72  6862.4    70.1  6892.4      72  6962.4    72.8  6982.4    75.1
#Mann= 5 , 1 , 0
  4129.6      .2       0  4547.7      .1       0  4983.9    .025       0
  5016.4      .1       0  5494.7      .2       0
#XS Ineff= 2 , 0
       0  4274.6    73.4  6349.7       0    71.8
Permanent Ineff=
       F       F
Bank Sta=4983.9,5016.4
XS Rating Curve= 0
Exp/Cntr=.3,.1

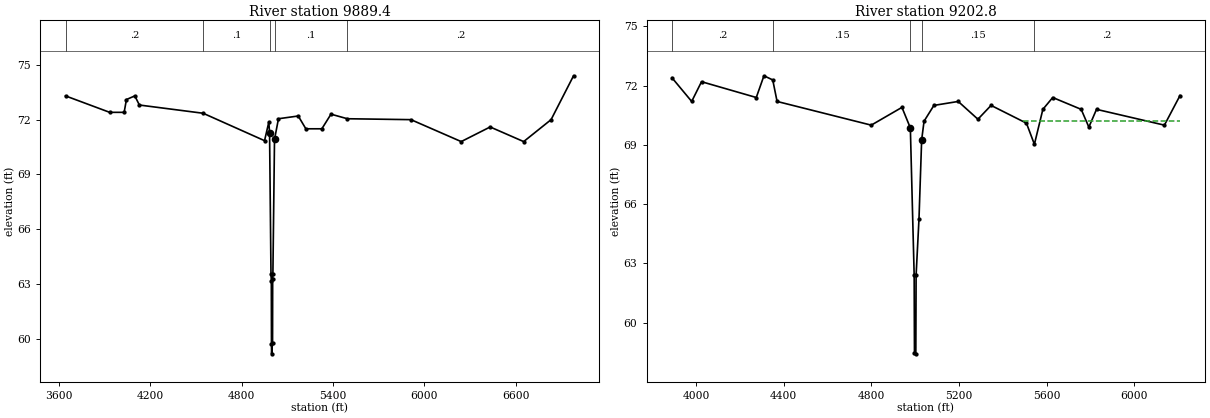
Type RM Length L Ch R = 1 ,9889.4  ,682,686.6,755.3
BEGIN DESCRIPTION:
Cross Section 9889.4
END DESCRIPTION:
XS GIS Cut Line= 4
      3075283.51     13852434.81      3075154.26     13851206.98
      3075098.87     13850985.42      3074692.67     13849157.52
#Sta/Elev= 30
  3644.2    73.3  3934.2    72.4  4029.2    72.4  4044.2    73.1  4099.2    73.3
  4129.2    72.8  4547.7   72.35    4951   70.85  4979.1   71.87  4983.9   71.29
  4993.3   63.53  4995.5    63.2  4996.4   59.72  4997.3   59.19  5003.6   59.79
  5004.3   63.27  5005.8   63.57  5016.4   70.92  5042.4   72.05  5172.2    72.2
  5222.2    71.5  5327.2    71.5  5387.2    72.3  5494.7   72.05  5912.2      72
  6242.2    70.8  6432.2    71.6  6652.2    70.8  6832.2      72  6979.7    74.4
#Mann= 5 , 1 , 0
  3644.2      .2       0  4547.7      .1       0  4983.9    .025       0
  5016.4      .1       0  5494.7      .2       0
Bank Sta=4983.9,5016.4
XS Rating Curve= 0
Exp/Cntr=.3,.1

Type RM Length L Ch R = 1 ,9202.8  ,68.7,70.8,80.3
BEGIN DESCRIPTION:
Cross Section 9202.8-Interpolated
END DESCRIPTION:
XS GIS Cut Line= 6
      3075748.41     13852040.57      3075799.99     13851016.69
      3075792.84     13850930.93      3075768.54     13850802.28
      3075765.98     13850510.61      3075728.06      13849725.3
#Sta/Elev= 30
  3889.5    72.4  3979.5    71.2  4024.5    72.2  4274.5    71.4  4309.5    72.5
  4349.7   72.29  4369.5    71.2  4799.5      70  4939.7    70.9  4978.1   69.86
  4995.5   62.42  4996.9   58.45  5003.1   58.42  5004.4    62.4  5017.6   65.26
  5029.7   69.25  5040.7    70.2  5085.7      71  5196.7    71.2  5286.7    70.3
  5346.7      71  5508.3    70.1  5544.6   69.03  5583.3    70.8  5628.3    71.4
  5758.3    70.8  5793.3    69.9  5828.3    70.8  6138.3      70  6209.6    71.5
#Mann= 5 , 1 , 0
  3889.5      .2       0  4349.7     .15       0  4978.1    .025       0
  5029.7     .15       0  5544.6      .2       0
#XS Ineff= 2 , 0
       0                  5491.3       0    70.2
Permanent Ineff=
       F       F
Bank Sta=4978.1,5029.7
XS Rating Curve= 0
Exp/Cntr=.5,.3