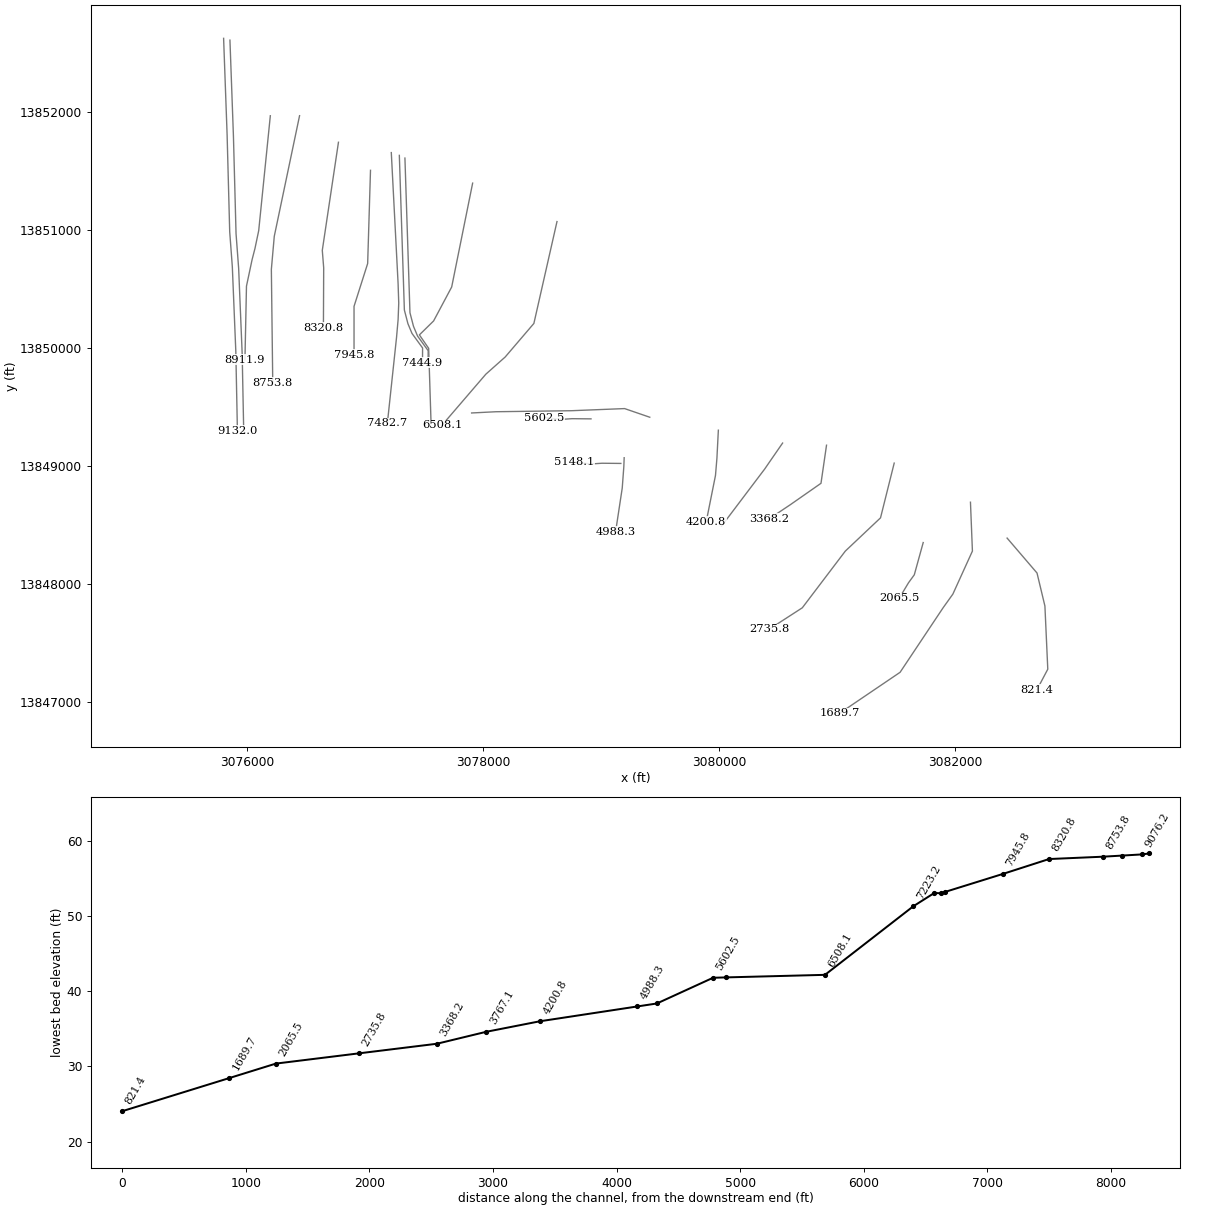
HEC-RAS study W140-01-00.PRJ: W140-01-00

--- W140-01-00.g01 (geometry) --- (continued)

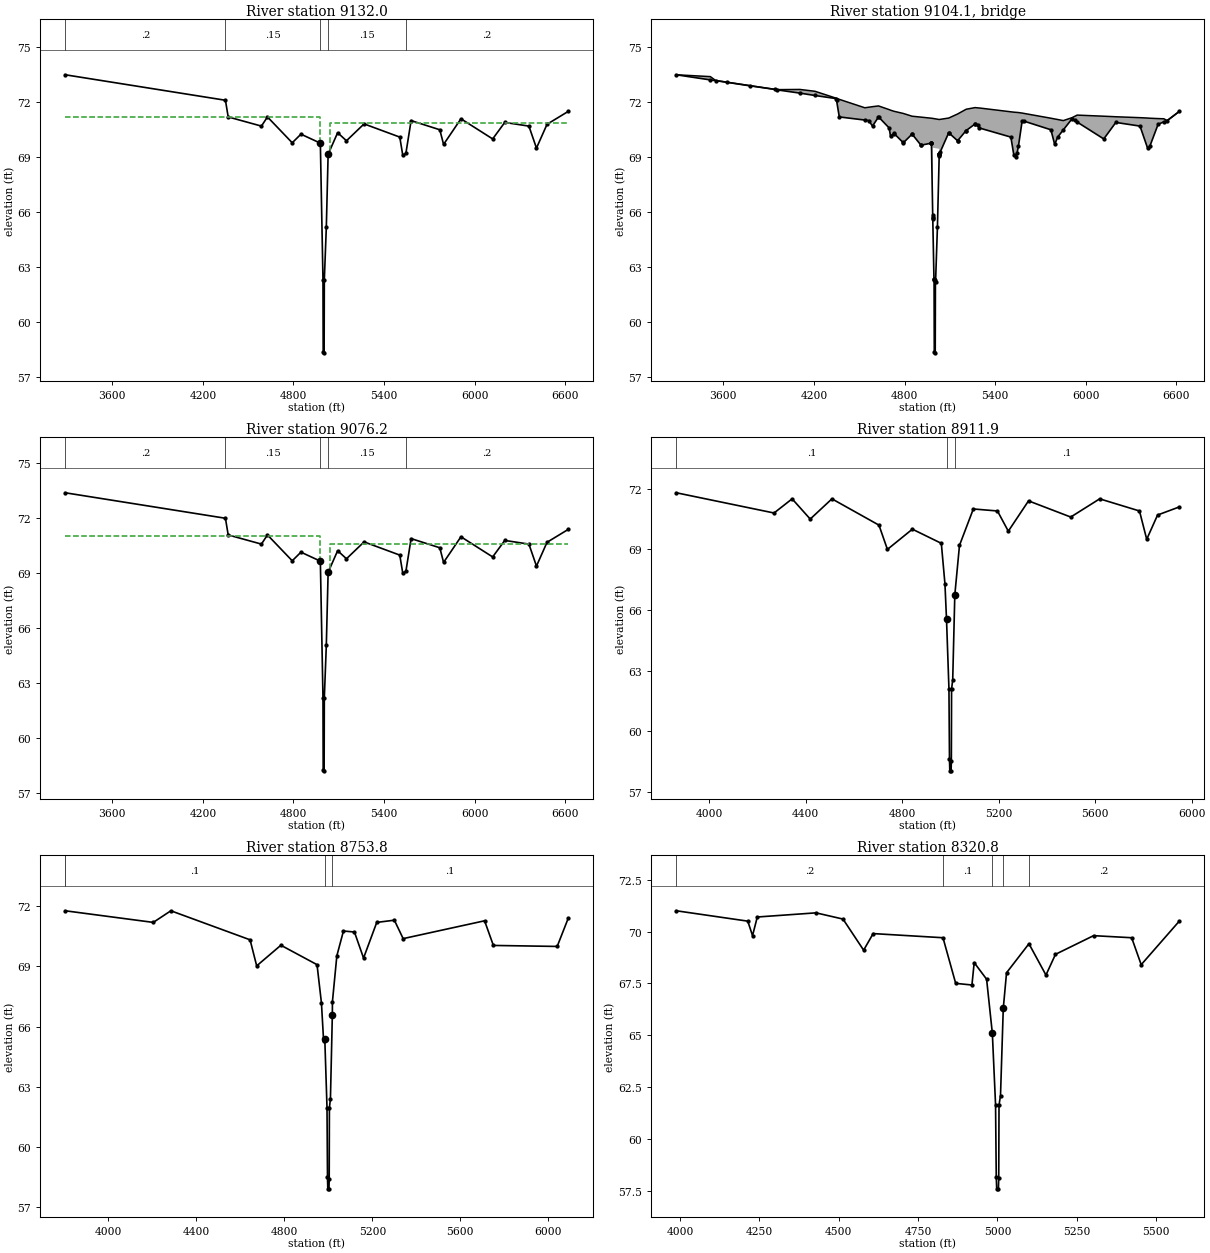
Type RM Length L Ch R = 1 ,9132.0  ,55.8,55.8,55.8
BEGIN DESCRIPTION:
Upstream Section of Bridge/Culvert/Weir
END DESCRIPTION:
XS GIS Cut Line= 6
      3075803.19     13852622.43      3075832.73     13851810.03
      3075854.89     13850982.86      3075877.05     13850687.44
      3075906.59     13849971.05      3075920.19     13849295.02
#Sta/Elev= 30
  3289.1   73.51  4349.7   72.12  4367.9   71.21  4587.9   70.71  4627.9   71.21
  4791.9    69.8  4849.7   70.27  4978.1   69.78  4995.5   62.34  4996.9   58.37
  5003.1   58.34  5004.4   62.32  5017.6   65.18  5029.6   69.17  5092.6   70.35
    5151   69.91  5267.6   70.83    5504   70.11    5524   69.11  5544.6   69.23
    5579   71.01    5769   70.51    5794   69.71    5909   71.11    6119   70.01
    6199   70.91    6359   70.71    6409   69.51    6479   70.81    6619   71.51
#Mann= 5 , 1 , 0
  3289.1      .2       0  4349.7     .15       0  4978.1    .025       0
  5029.6     .15       0  5544.6      .2       0
#XS Ineff= 2 , 0
       0    4977    71.2    5040       0    70.9
Permanent Ineff=
       F       F
Bank Sta=4978.1,5029.6
XS Rating Curve= 0
Exp/Cntr=.5,.3

Type RM Length L Ch R = 3 ,9104.1  ,,,
BEGIN DESCRIPTION:
FRIES ROAD
Structure ID: W41-7
END DESCRIPTION:
Bridge Culvert--1,0,-1,-1, 0
Deck Dist Width WeirC Skew NumUp NumDn MinLoCord MaxHiCord MaxSubmerge Is_Ogee
10,35.8,2.6,0, 50, 50, , , .95, 0, 1,1,,
  3289.1  3514.1  3549.1  3954.1    4107    4207  4347.9  4367.9    4537  4562.9
  4587.9  4627.9  4697.9  4707.1  4729.6  4791.9  4849.7  4908.7  4978.1 4986.83
  4986.9 5029.49  5029.6  5029.7  5092.6    5151    5208  5267.6  5289.5    5294
    5504    5524    5539    5554    5579    5769    5794    5814  5850.8    5909
  5942.8    6119    6199    6359    6409    6424    6479  6516.9    6539    6619
    73.5    73.4   73.19   72.69    72.7    72.6   72.22   72.16    71.7   71.73
   71.76    71.8    71.6   71.57   71.51   71.39   71.24   71.19   71.13   71.12
   71.12   71.06   71.06   71.06   71.14   71.36   71.62   71.71   71.69   71.69
   71.48   71.46   71.45   71.44   71.41   71.13   71.09   71.06      71   71.16
    71.3   71.24   71.21   71.16   71.14   71.13   71.11    71.1      71    71.5
    73.5   73.22   73.18   72.68    72.5   72.37    72.2    71.2   71.03      71
    70.7    71.2    70.6   70.15    70.3   69.79   70.26   69.66   69.77   65.68
   69.52   69.46   69.16   69.16   70.34    69.9   70.46   70.82   70.76    70.6
    70.1    69.1      69    69.6      71    70.5    69.7    70.1   70.49    71.1
   70.92      70    70.9    70.7    69.5    69.6    70.8   70.93      71    71.5
  3289.1  3514.1  3549.1  3954.1    4107    4207  4347.9  4367.9    4537  4562.9
  4587.9  4627.9  4697.9  4707.1  4729.6  4791.9  4849.7  4908.7  4978.1 4986.83
  4986.9 5029.49  5029.6  5029.7  5092.6    5151    5208  5267.6  5289.5    5294
    5504    5524    5539    5554    5579    5769    5794    5814  5850.8    5909
  5942.8    6119    6199    6359    6409    6424    6479  6516.9    6539    6619
    73.5    73.4   73.19   72.69    72.7    72.6   72.22   72.16    71.7   71.73
   71.76    71.8    71.6   71.57   71.51   71.39   71.24   71.19   71.13   71.12
   71.12   71.06   71.06   71.06   71.14   71.36   71.62   71.71   71.69   71.69
   71.48   71.46   71.45   71.44   71.41   71.13   71.09   71.06      71   71.16
    71.3   71.24   71.21   71.16   71.14   71.13   71.11    71.1      71    71.5
   73.39   73.11   73.07   72.57   72.39   72.26   72.09   71.09   70.92   70.89
   70.59   71.09   70.49   70.04   70.19   69.68   70.15   69.55   69.66   65.57
   69.41   69.35   69.05   69.05   70.23   69.79   70.35   70.71   70.65   70.49
   69.99   68.99   68.89   69.49   70.89   70.39   69.59   69.99   70.38   70.99
   70.81   69.89   70.79   70.59   69.39   69.49   70.69   70.82   70.89   71.39
BR Coef= 1 , 1 , 0 ,1.25, 0 ,,,.8,0,2,0,
WSPro=,,,, 1 ,,,, 0 ,,,, 0 ,,,,-1 ,-1 ,-1 , 0 , 0 , 0 , 0 , 0
BR U #Sta/Elev= 84
  3289.1    73.5  3514.1   73.22  3549.1   73.18  3624.1   73.09  3774.1    72.9
  3944.1    72.7  3954.1   72.68    4107    72.5    4207   72.37  4347.9    72.2
  4349.7   72.11  4367.9    71.2    4537   71.03  4562.9      71  4587.9    70.7
    4627   71.19  4627.9    71.2  4697.9    70.6  4707.1   70.15  4729.6    70.3
  4732.5   70.28  4789.4   69.81  4791.9   69.79  4849.7   70.26  4851.1   70.25
  4908.7   69.66  4909.9   69.66 4977.49   69.77  4977.6   69.77 4977.71   69.77
  4978.1   69.77  4986.4   65.86 4986.71   65.73 4986.83   65.68  4986.9   65.65
  4994.8   62.34  4994.9   62.34  4995.5   62.33  4996.9   58.36  5003.1   58.33
  5004.4   62.31  5005.3   62.19  5017.6   65.17  5029.3   69.06 5029.49   69.12
  5029.6   69.16  5029.7   69.16 5030.49   69.18  5030.6   69.18 5030.71   69.18
  5034.7   69.26  5092.6   70.34  5093.6   70.33    5151    69.9  5152.3   69.91
    5208   70.46  5208.5   70.46  5267.6   70.82  5269.6   70.81  5289.5   70.76
    5294    70.6    5504    70.1    5524    69.1    5539      69  5544.6   69.22
    5554    69.6    5579      71  5590.8   70.97    5769    70.5    5794    69.7
    5814    70.1  5850.8   70.49    5909    71.1  5925.8   71.01  5942.8   70.92
    6119      70    6199    70.9    6359    70.7    6409    69.5    6424    69.6
    6479    70.8  6516.9   70.93    6539      71    6619    71.5
BR U #Mann= 5
  3289.1      .2  4349.7     .15  4978.1    .025  5029.6     .15  5544.6      .2
BR U Banks=4978.1,5029.6
BR D #Sta/Elev= 84
  3289.1   73.39  3514.1   73.11  3549.1   73.07  3624.1   72.98  3774.1   72.79
  3944.1   72.59  3954.1   72.57    4107   72.39    4207   72.26  4347.9   72.09
  4349.7      72  4367.9   71.09    4537   70.92  4562.9   70.89  4587.9   70.59
    4627   71.08  4627.9   71.09  4697.9   70.49  4707.1   70.04  4729.6   70.19
  4732.5   70.17  4789.4    69.7  4791.9   69.68  4849.7   70.15  4851.1   70.14
  4908.7   69.55  4909.9   69.55 4977.49   69.66  4977.6   69.66 4977.71   69.66
  4978.1   69.66  4986.4   65.75 4986.71   65.62 4986.83   65.57  4986.9   65.54
  4994.8   62.23  4994.9   62.23  4995.5   62.22  4996.9   58.25  5003.1   58.22
  5004.4    62.2  5005.3   62.08  5017.6   65.06  5029.3   68.95 5029.49   69.01
  5029.6   69.05  5029.7   69.05 5030.49   69.07  5030.6   69.07 5030.71   69.07
  5034.7   69.15  5092.6   70.23  5093.6   70.22    5151   69.79  5152.3    69.8
    5208   70.35  5208.5   70.35  5267.6   70.71  5269.6    70.7  5289.5   70.65
    5294   70.49    5504   69.99    5524   68.99    5539   68.89  5544.6   69.11
    5554   69.49    5579   70.89  5590.8   70.86    5769   70.39    5794   69.59
    5814   69.99  5850.8   70.38    5909   70.99  5925.8    70.9  5942.8   70.81
    6119   69.89    6199   70.79    6359   70.59    6409   69.39    6424   69.49
    6479   70.69  6516.9   70.82    6539   70.89    6619   71.39
BR D #Mann= 5
  3289.1      .2  4349.7     .15  4978.1    .025  5029.6     .15  5544.6      .2
BR D Banks=4978.1,5029.6
BC Design=,, 0 ,, 0 ,,,,,,
BC HTab HWMax=73.51

Type RM Length L Ch R = 1 ,9076.2  ,164.3,164.3,164.3
BEGIN DESCRIPTION:
Downstream Section of Bridge/Culvert/Weir
END DESCRIPTION:
XS GIS Cut Line= 6
      3075856.87     13852607.23      3075886.41     13851794.83
      3075908.57     13850967.66      3075930.73     13850672.24
      3075960.27     13849955.85      3075973.88     13849279.81
#Sta/Elev= 30
  3289.1   73.38  4349.7   71.99  4367.9   71.08  4587.9   70.58  4627.9   71.08
  4791.9   69.67  4849.7   70.14  4978.1   69.65  4995.5   62.21  4996.9   58.24
  5003.1   58.21  5004.4   62.19  5017.6   65.05  5029.6   69.04  5092.6   70.22
    5151   69.78  5267.6    70.7    5504   69.98    5524   68.98  5544.6    69.1
    5579   70.88    5769   70.38    5794   69.58    5909   70.98    6119   69.88
    6199   70.78    6359   70.58    6409   69.38    6479   70.68    6619   71.38
#Mann= 5 , 1 , 0
  3289.1      .2       0  4349.7     .15       0  4978.1    .025       0
  5029.6     .15       0  5544.6      .2       0
#XS Ineff= 2 , 0
       0    4977      71    5040       0    70.6
Permanent Ineff=
       F       F
Bank Sta=4978.1,5029.6
XS Rating Curve= 0
Exp/Cntr=.5,.3

Type RM Length L Ch R = 1 ,8911.9  ,154.4,158.1,162.3
BEGIN DESCRIPTION:
Cross Section 8911.9-Interpolated
END DESCRIPTION:
XS GIS Cut Line= 6
      3076199.11     13851966.45      3076100.59     13850992.85
      3076068.72     13850840.88      3076044.42     13850746.54
      3075996.99     13850522.75      3075984.01     13849897.92
#Sta/Elev= 30
  3863.8    71.8  4268.8    70.8  4343.8    71.5  4418.8    70.5  4508.8    71.5
  4703.8    70.2  4738.8      69  4842.3      70  4962.3    69.3  4977.3    67.3
  4983.8   65.55  4993.9   62.11  4996.1   58.63  4997.5   58.06  5002.9   58.05
  5003.9   58.55  5004.8   62.09  5009.5   62.55  5018.2   66.75  5037.6    69.2
    5095      71    5195    70.9    5240    69.9  5323.8    71.4  5498.8    70.6
  5618.8    71.5  5783.8    70.9  5813.8    69.5  5858.8    70.7  5948.8    71.1
#Mann= 3 , 1 , 0
  3863.8      .1       0  4983.8     .04       0  5018.2      .1       0
Bank Sta=4983.8,5018.2
XS Rating Curve= 0
Exp/Cntr=.3,.1

Type RM Length L Ch R = 1 ,8753.8  ,425.8,433,441.7
BEGIN DESCRIPTION:
Cross Section 8753.8-Interpolated
END DESCRIPTION:
XS GIS Cut Line= 4
      3076446.88     13851966.95      3076232.56     13850944.84
      3076207.83     13850664.58      3076219.61     13849704.65
#Sta/Elev= 30
  3804.3   71.78  4204.3    71.2  4284.3   71.78  4644.3   70.33  4674.3   69.03
  4784.3   70.06  4948.6   69.09  4968.6   67.18  4978.6   65.26  4983.8    65.4
  4993.9   61.96  4996.1   58.48  4997.5   57.91  5002.9    57.9  5003.9    58.4
  5004.8   61.94  5009.5    62.4  5018.2    66.6  5018.6   67.25  5038.6   69.53
  5068.6   70.77  5118.6   70.72    5160   69.42    5220    71.2    5300   71.31
    5340   70.39    5710   71.28    5750   70.05    6040      70    6090    71.4
#Mann= 4 , 1 , 0
  3804.3      .2       0  3804.3      .1       0  4983.8     .04       0
  5018.2      .1       0
Bank Sta=4983.8,5018.2
XS Rating Curve= 0
Exp/Cntr=.3,.1

Type RM Length L Ch R = 1 ,8320.8  ,391.4,375,365.3
BEGIN DESCRIPTION:
Cross Section 8320.8
END DESCRIPTION:
XS GIS Cut Line= 4
      3076776.45     13851741.89      3076639.48     13850825.93
      3076651.29     13850678.22      3076648.99     13850168.15
#Sta/Elev= 30
  3988.3      71  4213.3    70.5  4228.3    69.8  4243.3    70.7  4428.3    70.9
  4513.3    70.6  4578.3    69.1  4608.3    69.9  4828.3    69.7  4868.3    67.5
  4919.5   67.42  4926.6    68.5  4965.7    67.7  4983.8   65.09  4993.9   61.65
  4996.1   58.17  4997.5    57.6  5002.9   57.59  5003.9   58.09  5004.8   61.63
  5009.5   62.09  5018.2   66.29  5028.5   68.01  5099.1   69.41  5152.7    67.9
  5182.7    68.9  5302.7    69.8  5422.7    69.7  5452.7    68.4  5572.7    70.5
#Mann= 5 , 1 , 0
  3988.3      .2       0  4828.3      .1       0  4983.8     .04       0
  5018.2      .1       0  5099.1      .2       0
Bank Sta=4983.8,5018.2
XS Rating Curve= 0
Exp/Cntr=.3,.1

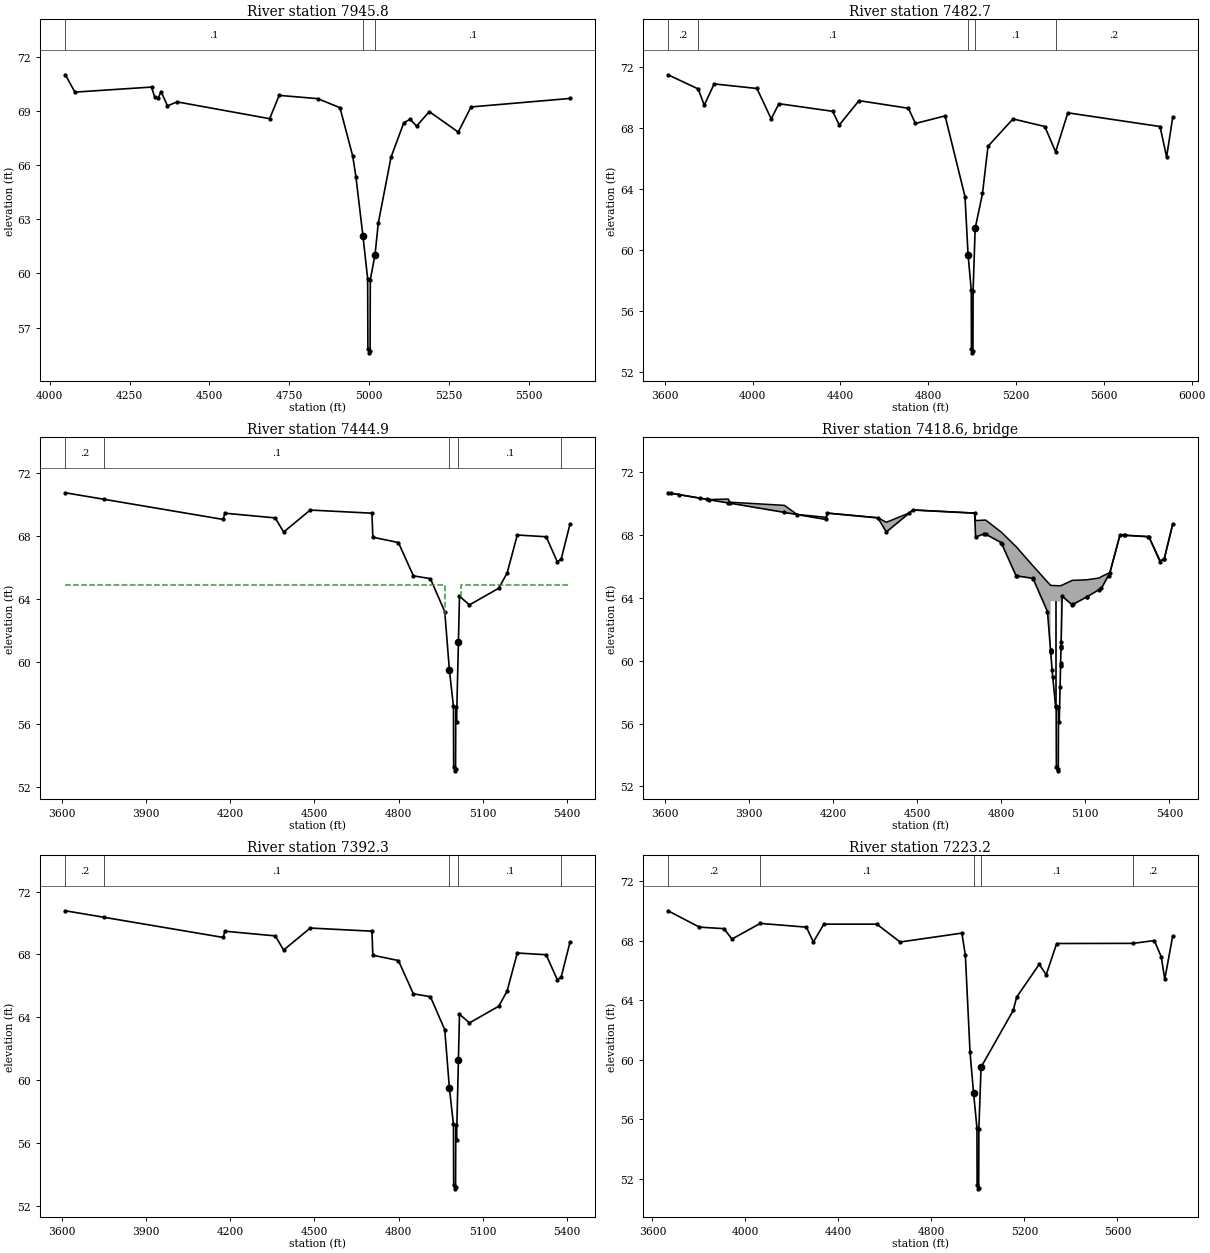
Type RM Length L Ch R = 1 ,7945.8  ,421.5,463.1,472.2
BEGIN DESCRIPTION:
Cross Section 7945.8-Interpolated
END DESCRIPTION:
XS GIS Cut Line= 4
      3077047.99       13851504.      3077023.87     13850714.04
      3076908.47     13850351.36      3076908.47     13849941.38
#Sta/Elev= 30
  4048.8   70.99  4078.8   70.03  4318.8   70.31  4328.8   69.76  4338.8   69.68
  4348.8   70.05  4368.8   69.27  4398.8   69.49  4688.8   68.56  4718.8   69.85
  4839.1   69.67  4909.1   69.17  4949.1   66.49  4959.1   65.35  4981.3   62.04
  4995.9    59.7  4996.6   55.83  5000.7    55.6  5003.5   55.69  5004.1   59.64
  5019.1   61.04  5029.1   62.77  5069.1   66.43  5109.1   68.33  5129.1   68.53
  5149.1   68.15  5189.1   68.95  5279.7   67.82  5319.7   69.21  5629.7   69.68
#Mann= 3 , 1 , 0
  4048.8      .1       0  4981.3     .04       0  5019.1      .1       0
Bank Sta=4981.3,5019.1
XS Rating Curve= 0
Exp/Cntr=.3,.1

Type RM Length L Ch R = 1 ,7482.7  ,37.5,37.8,39.1
BEGIN DESCRIPTION:
Cross Section 7482.7-Interpolated
END DESCRIPTION:
XS GIS Cut Line= 6
      3077224.21     13851654.24      3077281.85      13850543.4
      3077287.28     13850377.93      3077281.85     13850238.23
      3077268.29     13850084.96      3077190.98     13849361.36
#Sta/Elev= 30
  3614.3    71.5  3751.5   70.57  3779.3    69.5  3824.3    70.9  4019.3    70.6
  4084.3    68.6  4119.3    69.6  4364.3    69.1  4394.3    68.2  4484.3    69.8
  4709.3    69.3  4741.6    68.3  4876.6    68.8  4967.2    63.5  4981.3   59.67
  4995.9   57.33  4996.6   53.46  5000.7   53.23  5003.5   53.32  5004.1   57.27
  5013.6   61.41    5047    63.7    5072    66.8  5185.9    68.6  5330.9    68.1
  5380.1   66.44  5435.9      69  5855.9    68.1  5885.9    66.1  5913.6    68.7
#Mann= 5 , 1 , 0
  3614.3      .2       0  3751.5      .1       0  4981.3     .05       0
  5013.6      .1       0  5380.1      .2       0
Bank Sta=4981.3,5013.6
XS Rating Curve= 0
Exp/Cntr=.5,.3

Type RM Length L Ch R = 1 ,7444.9  ,52.6,52.6,52.6
BEGIN DESCRIPTION:
Upstream Section of Bridge/Culvert/Weir
END DESCRIPTION:
XS GIS Cut Line= 6
      3077292.36     13851630.61      3077335.03     13850320.07
      3077364.95     13850204.89      3077399.44     13850122.11
      3077489.36     13849998.47      3077488.49     13849871.84
#Sta/Elev= 30
  3611.9   70.75  3751.5   70.33  4175.3   69.05  4180.3   69.45  4360.3   69.15
  4390.3   68.25  4485.3   69.65  4705.3   69.45  4708.4   67.92  4799.6   67.58
    4853   65.46  4913.6   65.28  4964.9   63.18  4981.3   59.48  4995.9   57.14
  4996.6   53.27  5000.7   53.04  5003.5   53.13  5004.1   57.08  5006.8   56.16
  5013.6   61.22  5017.4   64.16    5053   63.61  5157.4   64.67  5187.3   65.64
  5223.5   68.06  5326.4   67.95  5366.4   66.35  5380.1   66.53  5411.4   68.75
#Mann= 5 , 1 , 0
  3611.9      .2       0  3751.5      .1       0  4981.3     .05       0
  5013.6      .1       0  5380.1      .2       0
#XS Ineff= 2 , 0
       0    4966    64.9    5022       0    64.9
Permanent Ineff=
       F       F
Bank Sta=4981.3,5013.6
XS Rating Curve= 0
Exp/Cntr=.5,.3

Type RM Length L Ch R = 3 ,7418.6  ,,,
BEGIN DESCRIPTION:
VOSS ROAD
Structure ID: W41-6
END DESCRIPTION:
Bridge Culvert--1,0,-1,-1, 0
Deck Dist Width WeirC Skew NumUp NumDn MinLoCord MaxHiCord MaxSubmerge Is_Ogee
10,32.6,2.6,0, 36, 36, , , .95, 0, 1,1,,
  3611.9  3756.9  3826.9  3831.9  4026.9  4071.9  4175.3  4180.3  4360.3  4390.3
  4471.5  4485.3  4705.3  4708.4  4740.1  4744.6  4799.6    4853    4913  4964.9
 4976.21  4976.3  5003.5 5011.59  5011.7  5017.4    5053  5104.8  5148.8  5157.4
  5187.3  5223.5  5326.4  5366.4  5381.4  5411.4
    70.7   70.27    70.3    70.1    69.9   69.32   69.14   69.41   69.11   68.82
   69.41   69.61   69.41   68.93   68.96   68.96    68.2   67.27   66.05   65.02
    64.8    64.8   64.78   64.78   64.78   64.82   65.12   65.16   65.27   65.36
   65.62   68.02   67.91   66.38    66.5    68.7
    70.7   70.26   70.05   70.04   69.45   69.31      69    69.4    69.1    68.2
    69.4    69.6    69.4   67.87    68.1   68.06   67.53   65.41   65.25   63.13
   60.58    63.8   63.78   63.78   59.76   64.11   63.56   64.06   64.53   64.62
   65.59   68.01    67.9    66.3    66.5    68.7
  3611.9  3756.9  3826.9  3831.9  4026.9  4071.9  4175.3  4180.3  4360.3  4390.3
  4471.5  4485.3  4705.3  4708.4  4740.1  4744.6  4799.6    4853    4913  4964.9
 4976.21  4976.3  5003.5 5011.59  5011.7  5017.4    5053  5104.8  5148.8  5157.4
  5187.3  5223.5  5326.4  5366.4  5381.4  5411.4
   70.77   70.33    70.3   70.11    69.9   69.38   69.14   69.47   69.17   68.82
   69.47   69.67   69.47   68.93   68.96   68.96    68.2   67.27   66.05   65.02
    64.8    64.8   64.78   64.78   64.78   64.82   65.12   65.16   65.27   65.36
   65.66   68.08   67.97   66.38   66.57   68.77
   70.77   70.33   70.12   70.11   69.52   69.38   69.07   69.47   69.17   68.27
   69.47   69.67   69.47   67.94   68.17   68.13    67.6   65.48   65.32    63.2
   60.65   63.87   63.85   63.85   59.83   64.18   63.63   64.13    64.6   64.69
   65.66   68.08   67.97   66.37   66.57   68.77
Pier Skew, UpSta & Num, DnSta & Num=  ,4993.9, 2 ,4993.9, 2 , 0 , 0 , 0 ,,
       1       1
   56.08   64.79
       1       1
   56.15   64.86
Abutment Skew #Up #Dn= , 2 , 2
  4976.1  4983.9
    63.8   58.94
  4976.1  4983.9
   63.87   59.01
Abutment Skew #Up #Dn= , 2 , 2
  5009.8 5011.79
   58.34   63.78
  5009.8 5011.79
   58.41   63.85
BR Coef= 1 , 1 , 0 ,1.25, 0 ,,,.8,0,2,0,
WSPro=,,,, 1 ,,,, 0 ,,,, 0 ,,,,-1 ,-1 ,-1 , 0 , 0 , 0 , 0 , 0
BR U #Sta/Elev= 68
  3611.9    70.7  3621.9   70.67  3651.9   70.58  3726.9   70.35  3751.5   70.28
  3756.9   70.26  3826.9   70.05  3831.9   70.04  4026.9   69.45  4071.9   69.31
  4175.3      69  4180.3    69.4  4360.3    69.1  4390.3    68.2  4471.5    69.4
  4485.3    69.6  4705.3    69.4  4708.4   67.87  4740.1    68.1  4744.6   68.06
  4799.6   67.53  4802.6   67.41    4853   65.41    4857    65.4    4913   65.25
  4913.6   65.23  4964.9   63.13 4975.69    60.7  4975.8   60.67 4975.91   60.65
  4976.1    60.6 4976.21   60.58  4976.3   60.56  4981.3   59.43  4983.9   58.94
  4993.9   57.07  4995.9   57.09  4996.6   53.22  5000.7   52.99  5003.5   53.08
  5004.1   57.03  5006.8   56.11  5009.8   58.34 5011.59   59.67  5011.7   59.76
  5011.8   59.83 5013.09   60.79  5013.2   60.87 5013.31   60.95  5013.6   61.17
  5017.4   64.11    5053   63.56  5055.9   63.59  5104.6   64.06  5104.8   64.06
  5148.8   64.53  5157.4   64.62  5182.5   65.43  5187.3   65.59  5223.5   68.01
  5236.9      68  5241.9   67.99  5321.9    67.9  5326.4    67.9  5366.4    66.3
  5380.1   66.48  5381.4    66.5  5411.4    68.7
BR U #Mann= 5
  3611.9      .2  3751.5      .1  4981.3     .05  5013.6      .1  5380.1      .2
BR U Banks=4981.3,5013.6
BR D #Sta/Elev= 68
  3611.9   70.77  3621.9   70.74  3651.9   70.65  3726.9   70.42  3751.5   70.35
  3756.9   70.33  3826.9   70.12  3831.9   70.11  4026.9   69.52  4071.9   69.38
  4175.3   69.07  4180.3   69.47  4360.3   69.17  4390.3   68.27  4471.5   69.47
  4485.3   69.67  4705.3   69.47  4708.4   67.94  4740.1   68.17  4744.6   68.13
  4799.6    67.6  4802.6   67.48    4853   65.48    4857   65.47    4913   65.32
  4913.6    65.3  4964.9    63.2 4975.69   60.77  4975.8   60.74 4975.91   60.72
  4976.1   60.67 4976.21   60.65  4976.3   60.63  4981.3    59.5  4983.9   59.01
  4993.9   57.14  4995.9   57.16  4996.6   53.29  5000.7   53.06  5003.5   53.15
  5004.1    57.1  5006.8   56.18  5009.8   58.41 5011.59   59.74  5011.7   59.83
  5011.8    59.9 5013.09   60.86  5013.2   60.94 5013.31   61.02  5013.6   61.24
  5017.4   64.18    5053   63.63  5055.9   63.66  5104.6   64.13  5104.8   64.13
  5148.8    64.6  5157.4   64.69  5182.5    65.5  5187.3   65.66  5223.5   68.08
  5236.9   68.07  5241.9   68.06  5321.9   67.97  5326.4   67.97  5366.4   66.37
  5380.1   66.55  5381.4   66.57  5411.4   68.77
BR D #Mann= 5
  3611.9      .2  3751.5      .1  4981.3     .05  5013.6      .1  5380.1      .2
BR D Banks=4981.3,5013.6
BC Design=,, 0 ,, 0 ,,,,,,
BC HTab HWMax=70.75

Type RM Length L Ch R = 1 ,7392.3  ,169.1,169.1,169.1
BEGIN DESCRIPTION:
Downstream Section of Bridge/Culvert/Weir
END DESCRIPTION:
XS GIS Cut Line= 6
      3077339.72     13851607.73      3077382.39     13850297.19
      3077412.31     13850182.01       3077446.8     13850099.23
      3077536.72     13849975.59      3077535.86     13849848.97
#Sta/Elev= 30
  3611.9   70.78  3751.5   70.36  4175.3   69.08  4180.3   69.48  4360.3   69.18
  4390.3   68.28  4485.3   69.68  4705.3   69.48  4708.4   67.95  4799.6   67.61
    4853   65.49  4913.6   65.31  4964.9   63.21  4981.3   59.51  4995.9   57.17
  4996.6    53.3  5000.7   53.07  5003.5   53.16  5004.1   57.11  5006.8   56.19
  5013.6   61.25  5017.4   64.19    5053   63.64  5157.4    64.7  5187.3   65.67
  5223.5   68.09  5326.4   67.98  5366.4   66.38  5380.1   66.56  5411.4   68.78
#Mann= 5 , 1 , 0
  3611.9      .2       0  3751.5      .1       0  4981.3     .05       0
  5013.6      .1       0  5380.1      .2       0
#XS Ineff= 2 , 0
       0    4966    62.6    5022       0    62.6
Permanent Ineff=
       F       F
Bank Sta=4981.3,5013.6
XS Rating Curve= 0
Exp/Cntr=.5,.3

Type RM Length L Ch R = 1 ,7223.2  ,695.6,715.1,712
BEGIN DESCRIPTION:
Cross Section 7223.2-Interpolated
END DESCRIPTION:
XS GIS Cut Line= 6
      3077913.54     13851395.44       3077735.9     13850515.15
      3077582.75      13850227.6      3077462.25     13850109.38
      3077540.91     13849995.44      3077561.26     13849356.61
#Sta/Elev= 30
  3667.3      70  3802.3    68.9  3907.3    68.8  3942.3    68.1  4063.8   69.15
  4262.3    68.9  4292.3    67.9  4337.3    69.1  4565.3    69.1  4665.3    67.9
  4931.1    68.5  4946.1      67  4966.1    60.5  4981.3   57.75  4995.9   55.41
  4996.6   51.54  5000.7   51.31  5003.5    51.4  5004.1   55.35  5013.6   59.49
  5151.8    63.3  5166.8    64.2  5263.7    66.4  5293.7    65.7  5338.7    67.8
  5667.9   67.81  5758.7      68  5788.7    66.9  5803.7    65.4  5837.8    68.3
#Mann= 5 , 1 , 0
  3667.3      .2       0  4063.8      .1       0  4981.3     .05       0
  5013.6      .1       0  5667.9      .2       0
Bank Sta=4981.3,5013.6
XS Rating Curve= 0
Exp/Cntr=.3,.1

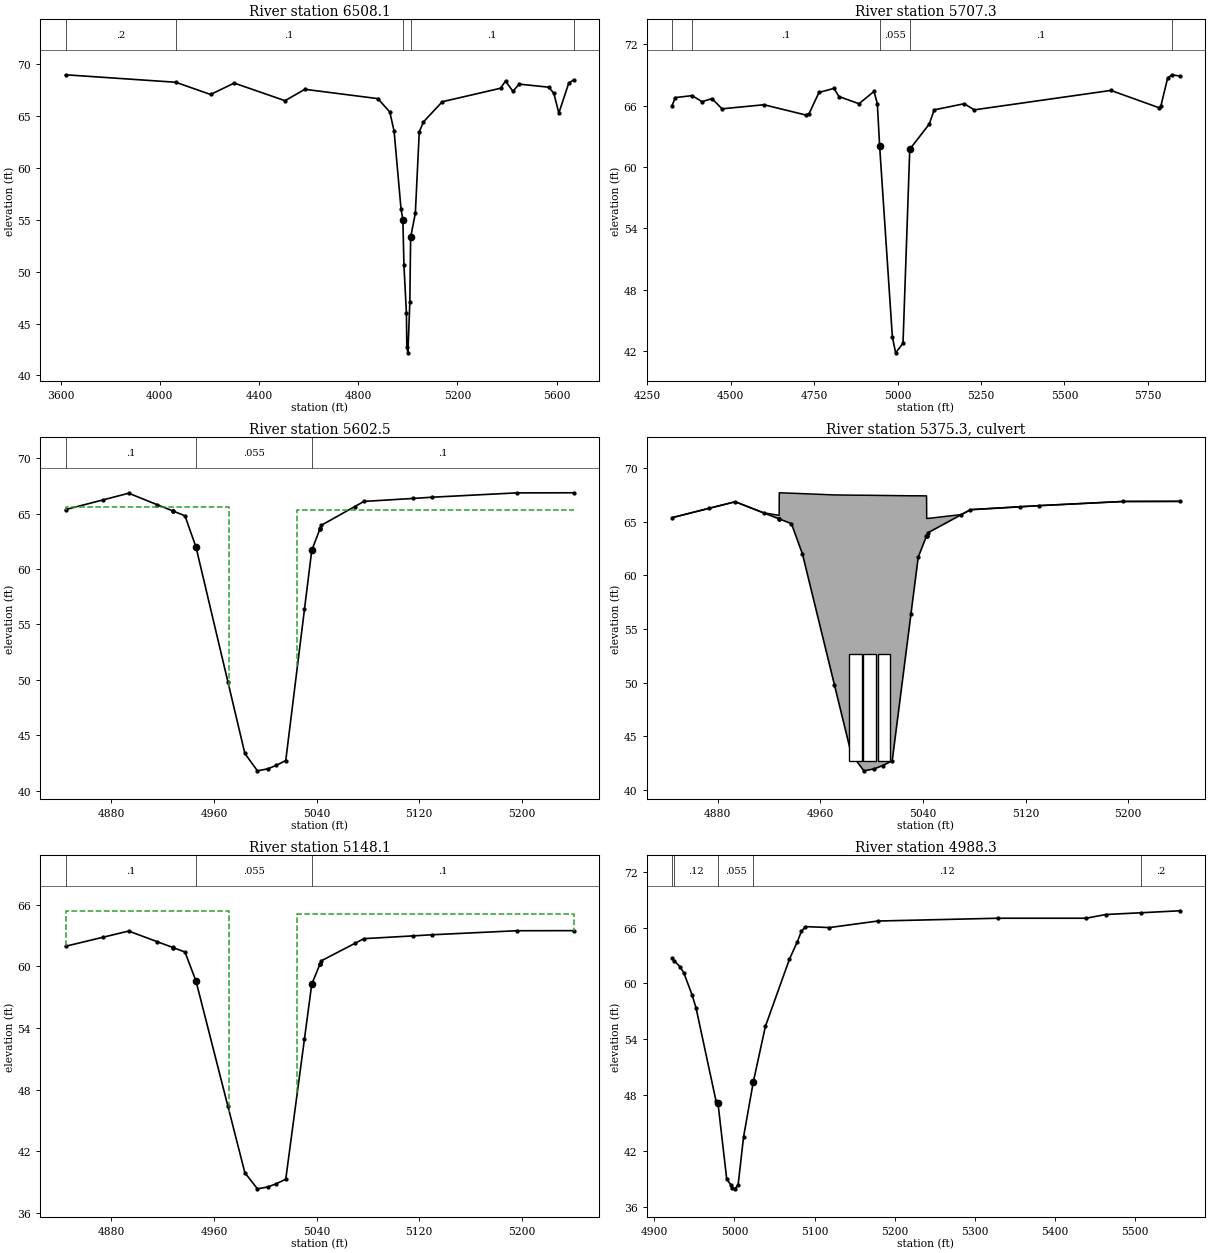
Type RM Length L Ch R = 1 ,6508.1  ,873.4,800.8,752.2
BEGIN DESCRIPTION:
Cross Section 6508.1
END DESCRIPTION:
XS GIS Cut Line= 5
      3078628.28     13851069.57      3078432.53     13850206.51
      3078189.44     13849922.13      3078025.22     13849776.17
      3077654.23     13849344.35
#Sta/Elev= 30
  3619.8      69  4063.8   68.28  4204.8    67.1  4299.8    68.2  4504.8    66.5
  4584.8    67.6  4878.9    66.7  4927.1   65.41  4944.5   63.56  4972.5   56.03
  4979.9   55.02  4984.1   50.64  4994.1   46.01  4995.8   42.75  5000.1   42.18
  5007.9   47.05  5011.1   53.32  5030.1   55.64  5045.9   63.49  5062.7   64.45
  5138.6    66.4  5373.6    67.7  5393.6    68.4  5423.6    67.4  5448.6    68.1
  5568.6    67.8  5588.6    67.2  5608.6    65.3  5648.6    68.2  5667.9    68.5
#Mann= 5 , 1 , 0
  3619.8      .2       0  4063.8      .1       0  4979.9     .05       0
  5011.1      .1       0  5667.9      .2       0
Bank Sta=4979.9,5011.1
XS Rating Curve= 0
Exp/Cntr=.3,.1

Type RM Length L Ch R = 1 ,5707.3  ,105.8,104.8,104.2
BEGIN DESCRIPTION:
Cross Section 5707.3-Interpolated
END DESCRIPTION:
XS GIS Cut Line= 5
      3079414.49     13849411.59      3079201.25     13849484.89
      3078751.18      13849466.9      3078111.73     13849458.24
      3077904.84     13849447.73
#Sta/Elev= 30
  4323.6      66  4333.6    66.8    4384   66.99  4413.6    66.4  4443.6    66.7
  4473.6    65.7  4599.1    66.1  4724.1    65.1  4734.1    65.2  4764.1    67.3
  4809.1    67.7  4824.1    66.9  4884.1    66.2  4929.1    67.4  4939.1    66.2
    4946   62.03  4984.1   43.41  4993.9   41.84    5016   42.77  5036.3   61.75
  5094.5    64.2  5109.5    65.6  5199.5    66.2  5229.5    65.6    5639    67.5
    5784    65.8    5789      66    5809    68.7  5821.8   69.03  5846.2    68.9
#Mann= 5 , 1 , 0
  4323.6      .2       0    4384      .1       0    4946    .055       0
  5036.3      .1       0  5821.8      .2       0
Bank Sta=4946,5036.3
XS Rating Curve= 0
Exp/Cntr=.5,.3

Type RM Length L Ch R = 1 ,5602.5  ,454.4,454.4,454.4
BEGIN DESCRIPTION:
Upstream Section of Bridge/Culvert/Weir
END DESCRIPTION:
XS GIS Cut Line= 4
      3078916.65     13849397.81      3078756.43     13849399.38
       3078665.2      13849393.3      3078521.36     13849408.52
#Sta/Elev= 27
  4844.2   65.37  4873.2   66.24  4893.5   66.85  4915.8   65.81 4927.79   65.26
  4927.9   65.25 4928.01   65.25  4937.4   64.81    4946   61.98  4970.9   49.81
  4984.1   43.36  4993.9   41.79  5001.9   41.97  5008.5   42.28    5016   42.72
  5030.6   56.37  5036.3    61.7 5042.69   63.63  5042.8   63.66 5042.91   63.69
  5043.8   63.96  5069.9   65.65    5077   66.11  5115.4   66.38  5130.3   66.49
    5196   66.88  5240.5   66.89
#Mann= 3 , 1 , 0
  4844.2      .1       0    4946    .055       0  5036.3      .1       0
#XS Ineff= 2 , 0
       0    4972    65.6    5025       0    65.3
Permanent Ineff=
       F       F
Bank Sta=4946,5036.3
XS Rating Curve= 0
Exp/Cntr=.5,.3

Type RM Length L Ch R = 2 ,5375.3  ,,,
BEGIN DESCRIPTION:
INTERSTATE 10
Structure ID: W41-4
END DESCRIPTION:
Bridge Culvert--1,0,-1,-1, 0
Deck Dist Width WeirC Skew NumUp NumDn MinLoCord MaxHiCord MaxSubmerge Is_Ogee
10,434.4,3,0, 27, 27, , , .95, 0, 1,1,,
  4844.2  4873.2  4893.5  4915.8 4927.79  4927.9 4928.01  4937.4    4946  4970.9
  4984.1  4993.9  5001.9  5008.5    5016  5030.6  5036.3 5042.69  5042.8 5042.91
  5043.8  5069.9    5077  5115.4  5130.3    5196  5240.5
   65.37   66.25   66.86   65.82   65.59   67.69   67.69   67.65   67.61   67.49
   67.47   67.46   67.45   67.44   67.43   67.41   67.41    67.4    67.4    65.3
    65.3   65.66   66.12   66.39   66.49   66.88   66.89
   65.37   66.24   66.85   65.81   65.26   65.25   65.25   64.81   61.98   49.81
   43.36   41.79   41.97   42.28   42.72   56.37    61.7   63.63   63.66   63.69
   63.96   65.65   66.11   66.38   66.49   66.88   66.89
  4844.2  4873.2  4893.5  4915.8 4927.79  4927.9 4928.01  4937.4    4946  4970.9
  4984.1  4993.9  5001.9  5008.5    5016  5030.6  5036.3 5042.69  5042.8 5042.91
  5043.8  5069.9    5077  5115.4  5130.3    5196  5240.5
   65.37   66.25   66.86   65.82   65.59   67.69   67.69   67.65   67.61   67.49
   67.47   67.46   67.45   67.44   67.43   67.41   67.41    67.4    67.4    65.3
    65.3   65.66   66.12   66.39   66.49   66.88   66.89
   61.98   62.85   63.46   62.42   61.87   61.86   61.86   61.42   58.59   46.42
   39.97    38.4   38.58   38.89   39.33   52.98   58.31   60.24   60.27    60.3
   60.57   62.26   62.72   62.99    63.1   63.49    63.5
BR Coef= 1 , 0 , 0 ,1.25, 0 ,,,.8,-1,2,0,
WSPro=,,,, 1 ,,,, 0 ,,,, 0 ,,,,-1 ,-1 ,-1 , 0 , 0 , 0 , 0 , 0
Culvert=2,10,10,434.4,.015,.4,1,8,1,42.68,4987.5,42.43,4987.5,Culvert #1  , 0 ,10
Culvert Bottom n=.015
Culvert=2,10,10,434.4,.015,.4,1,8,1,42.68,4998.5,42.43,4998.5,Culvert #2  , 0 ,10
Culvert Bottom n=.015
Culvert=2,10,10,434.4,.015,.4,1,8,1,42.68,5009.6,42.43,5009.6,Culvert #3  , 0 ,10
Culvert Bottom n=.015
BR U #Sta/Elev= 27
  4844.2   65.37  4873.2   66.24  4893.5   66.85  4915.8   65.81 4927.79   65.26
  4927.9   65.25 4928.01   65.25  4937.4   64.81    4946   61.98  4970.9   49.81
  4984.1   43.36  4993.9   41.79  5001.9   41.97  5008.5   42.28    5016   42.72
  5030.6   56.37  5036.3    61.7 5042.69   63.63  5042.8   63.66 5042.91   63.69
  5043.8   63.96  5069.9   65.65    5077   66.11  5115.4   66.38  5130.3   66.49
    5196   66.88  5240.5   66.89
BR U #Mann= 3
  4844.2      .1    4946    .055  5036.3      .1
BR U Banks=4946,5036.3
BR D #Sta/Elev= 27
  4844.2   61.98  4873.2   62.85  4893.5   63.46  4915.8   62.42 4927.79   61.87
  4927.9   61.86 4928.01   61.86  4937.4   61.42    4946   58.59  4970.9   46.42
  4984.1   39.97  4993.9    38.4  5001.9   38.58  5008.5   38.89    5016   39.33
  5030.6   52.98  5036.3   58.31 5042.69   60.24  5042.8   60.27 5042.91    60.3
  5043.8   60.57  5069.9   62.26    5077   62.72  5115.4   62.99  5130.3    63.1
    5196   63.49  5240.5    63.5
BR D #Mann= 3
  4844.2      .1    4946    .055  5036.3      .1
BR D Banks=4946,5036.3
BC Design=,, 0 ,, 0 ,,,,,,
BC HTab HWMax=66.89

Type RM Length L Ch R = 1 ,5148.1  ,159.8,159.8,159.8
BEGIN DESCRIPTION:
Downstream Section of Bridge/Culvert/Weir
END DESCRIPTION:
XS GIS Cut Line= 4
      3079169.34     13849020.15      3079009.11     13849021.72
      3078917.88     13849015.64      3078774.05     13849030.86
#Sta/Elev= 27
  4844.2   61.95  4873.2   62.82  4893.5   63.43  4915.8   62.39 4927.79   61.84
  4927.9   61.83 4928.01   61.83  4937.4   61.39    4946   58.56  4970.9   46.39
  4984.1   39.94  4993.9   38.37  5001.9   38.55  5008.5   38.86    5016    39.3
  5030.6   52.95  5036.3   58.28 5042.69   60.21  5042.8   60.24 5042.91   60.27
  5043.8   60.54  5069.9   62.23    5077   62.69  5115.4   62.96  5130.3   63.07
    5196   63.46  5240.5   63.47
#Mann= 3 , 1 , 0
  4844.2      .1       0    4946    .055       0  5036.3      .1       0
#XS Ineff= 2 , 0
       0    4972    65.4    5025       0    65.1
Permanent Ineff=
       F       F
Bank Sta=4946,5036.3
XS Rating Curve= 0
Exp/Cntr=.5,.3

Type RM Length L Ch R = 1 ,4988.3  ,786.7,787.5,790.4
BEGIN DESCRIPTION:
Cross Section 4988.3-Interpolated
END DESCRIPTION:
XS GIS Cut Line= 4
      3079197.65     13849068.48      3079194.59     13848991.78
      3079181.26     13848811.86      3079124.62     13848438.69
#Sta/Elev= 27
  4921.9    62.7  4924.7   62.45  4931.9    61.8  4936.9    61.1  4946.9    58.8
  4951.9    57.4  4976.9    47.4  4979.4   47.13  4990.3      39  4995.5    38.4
  4996.4   38.06  5000.4   37.97  5004.5   38.38  5011.3   43.52  5023.4    49.4
  5038.6    55.4  5068.6    62.6  5078.6    64.5  5083.6    65.6  5088.6    66.1
  5118.6      66    5179    66.7    5329      67    5439      67    5464    67.4
  5508.1   67.59  5556.5    67.8
#Mann= 5 , 1 , 0
  4921.9      .1       0  4924.7     .12       0  4979.4    .055       0
  5023.4     .12       0  5508.1      .2       0
Bank Sta=4979.4,5023.4
XS Rating Curve= 0
Exp/Cntr=.3,.1

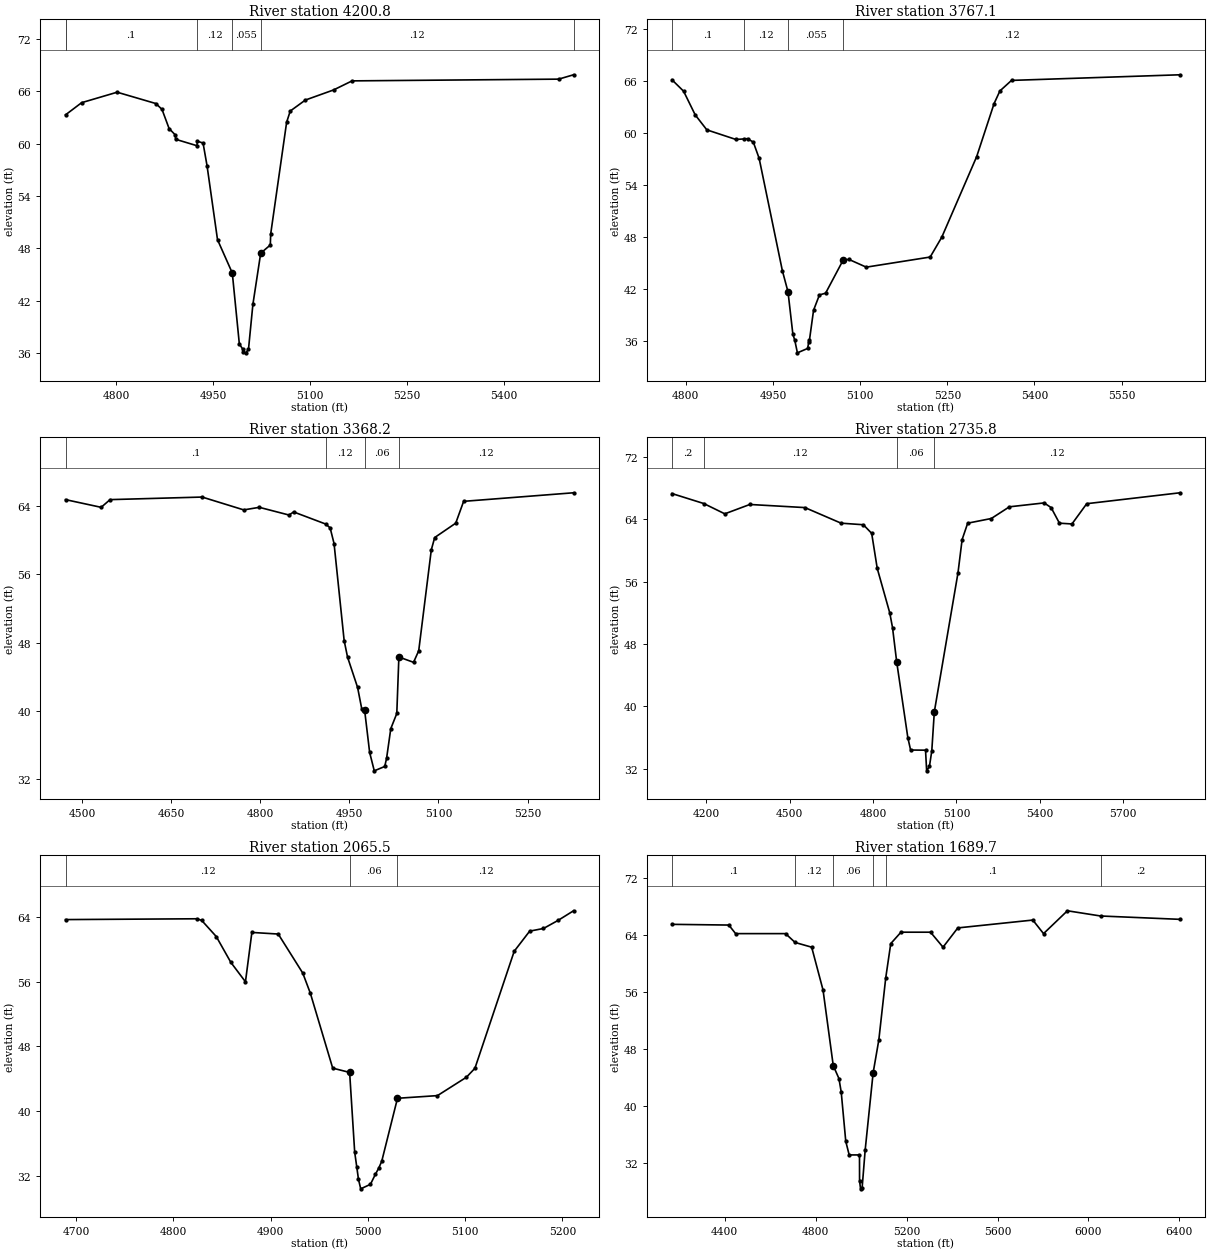
Type RM Length L Ch R = 1 ,4200.8  ,446.4,433.7,400.9
BEGIN DESCRIPTION:
Cross Section 4200.8
END DESCRIPTION:
XS GIS Cut Line= 4
      3079995.76     13849301.78       3079983.6     13849064.59
      3079971.43     13848918.62      3079892.37      13848523.3
#Sta/Elev= 30
    4721    63.3    4746    64.7    4801    65.9    4861    64.6  4870.5   63.93
  4881.5   61.73  4891.2   60.99  4891.6    60.5  4924.7   59.76  4925.2   60.28
  4934.1   60.07  4940.3   57.46  4956.5   48.98  4979.4   45.16  4990.3   37.03
  4995.5   36.43  4996.4   36.09  5000.4      36  5004.5   36.41  5011.3   41.55
  5023.4   47.43  5038.3   48.37  5038.9   49.64  5063.6   62.46  5069.2   63.74
  5092.6      65  5136.3   66.16    5165    67.2    5485    67.4  5508.1    67.9
#Mann= 6 , 1 , 0
    4721      .2       0    4721      .1       0  4924.7     .12       0
  4979.4    .055       0  5023.4     .12       0  5508.1      .2       0
Bank Sta=4979.4,5023.4
XS Rating Curve= 0
Exp/Cntr=.3,.1

Type RM Length L Ch R = 1 ,3767.1  ,413.6,398.9,382.5
BEGIN DESCRIPTION:
Cross Section 3767.1-Interpolated
END DESCRIPTION:
XS GIS Cut Line= 4
      3080540.12     13849192.67      3080431.21     13849035.16
      3080390.08     13848975.05      3080022.27     13848488.33
#Sta/Elev= 30
  4776.1   66.18  4796.1   64.86  4816.1   62.12  4836.1   60.39  4886.1   59.28
    4900   59.34  4906.1   59.37  4916.1   58.97  4926.1    57.1  4966.1    44.1
  4975.8   41.66  4984.2   36.75  4987.4   36.07    4992    34.6  5009.6   35.11
  5011.4   35.82  5012.7   36.06  5019.8   39.53  5029.9    41.3  5040.5    41.5
  5070.5    45.3  5080.5   45.41  5110.5   44.51  5220.5   45.68  5240.5   47.98
  5300.5   57.29  5330.5   63.43  5340.5   64.89  5360.5   66.11  5650.5   66.76
#Mann= 4 , 1 , 0
  4776.1      .1       0    4900     .12       0  4975.8    .055       0
  5070.5     .12       0
Bank Sta=4975.8,5070.5
XS Rating Curve= 0
Exp/Cntr=.3,.1

Type RM Length L Ch R = 1 ,3368.2  ,613.4,632.4,631.2
BEGIN DESCRIPTION:
Cross Section 3368.2
END DESCRIPTION:
XS GIS Cut Line= 4
      3080912.36      13849174.6      3080865.47     13848851.72
      3080603.95     13848669.26      3080429.35     13848552.65
#Sta/Elev= 30
  4472.3    64.7  4532.3    63.8  4547.3    64.7  4702.3      65  4772.3    63.5
  4798.5    63.8  4848.5    62.9  4856.3   63.26  4910.1   61.85  4917.7    61.4
  4924.3   59.57  4941.3   48.23    4947    46.3  4963.9   42.76    4971   40.22
  4975.8   40.07  4984.2   35.16    4992   33.01  5009.6   33.52  5012.7   34.47
  5019.8   37.94  5029.9   39.71  5033.4   46.31  5058.1   45.69  5066.8   47.04
    5088   58.84  5093.7   60.27  5129.1   61.95  5142.4    64.5  5327.4    65.5
#Mann= 4 , 1 , 0
  4472.3      .1       0  4910.1     .12       0  4975.8     .06       0
  5033.4     .12       0
Bank Sta=4975.8,5033.4
XS Rating Curve= 0
Exp/Cntr=.3,.1

Type RM Length L Ch R = 1 ,2735.8  ,621.1,670.3,643.9
BEGIN DESCRIPTION:
Cross Section 2735.8-Interpolated
END DESCRIPTION:
XS GIS Cut Line= 5
      3081485.91     13849022.94      3081369.93       13848559.
      3081071.68     13848277.32      3080707.16     13847796.81
      3080425.48     13847614.55
#Sta/Elev= 30
  4076.8    67.3  4191.2   66.02  4266.8    64.7  4356.8    65.9    4555    65.5
    4685    63.5    4765    63.3    4795    62.2    4815    57.7    4860      52
    4870    50.1    4885    45.7    4925      36    4935    34.4  4988.7   34.38
  4992.7   31.73  5002.7   32.29  5011.2   34.29  5020.3    39.3  5105.3    57.1
  5120.3    61.4  5140.3    63.5  5225.3    64.1  5290.3    65.6  5415.3    66.1
  5440.3    65.5  5470.3    63.5  5515.3    63.4  5568.4      66  5903.9    67.4
#Mann= 4 , 1 , 0
  4076.8      .2       0  4191.2     .12       0    4885     .06       0
  5020.3     .12       0
Bank Sta=4885,5020.3
XS Rating Curve= 0
Exp/Cntr=.3,.1

Type RM Length L Ch R = 1 ,2065.5  ,384.1,375.8,375.5
BEGIN DESCRIPTION:
Cross Section 2065.5
END DESCRIPTION:
XS GIS Cut Line= 4
      3081731.68      13848349.7      3081656.12     13848076.28
      3081607.46     13848009.38      3081527.26     13847875.69
#Sta/Elev= 29
  4689.2    63.7  4824.2    63.8  4829.2    63.6  4844.2    61.6  4859.2    58.4
  4874.2      56  4880.8   62.11  4907.9   61.91  4933.1   57.08  4940.9   54.59
  4963.9   45.31  4981.3   44.78  4986.5   34.91  4988.7   33.02  4990.4   31.54
  4992.7   30.37  5002.7   30.93  5007.7   32.15  5011.2   32.93  5014.3   33.78
  5030.5   41.58  5071.6   41.91  5101.3   44.18  5110.1   45.29  5150.5   59.78
  5166.4   62.27  5180.6    62.6  5195.6    63.6  5211.5   64.79
#Mann= 3 , 1 , 0
  4689.2     .12       0  4981.3     .06       0  5030.5     .12       0
Bank Sta=4981.3,5030.5
XS Rating Curve= 0
Exp/Cntr=.3,.1

Type RM Length L Ch R = 1 ,1689.7  ,764.2,868.3,909.5
BEGIN DESCRIPTION:
Cross Section 1689.7-Interpolated
END DESCRIPTION:
XS GIS Cut Line= 6
      3082132.11     13848691.55      3082148.68     13848277.32
      3081982.99      13847912.8      3081900.14     13847796.81
      3081535.62     13847250.03      3081021.97     13846902.08
#Sta/Elev= 30
  4167.7    65.5  4417.7    65.4  4447.7    64.2  4667.3    64.2  4709.5   62.96
  4782.3    62.3  4832.3    56.3  4877.3    45.7  4902.3    43.9  4912.3      42
  4932.3    35.1  4947.3    33.2  4992.7    33.2    4993   29.56  4997.4   28.45
  5004.2   28.56  5017.7    33.9  5052.7    44.7  5077.7    49.3  5108.2   58.02
  5130.2    62.8  5175.2    64.4  5305.2    64.4  5360.2    62.3  5425.2      65
  5755.2    66.1  5802.4    64.2  5907.4    67.4  6053.2   66.67  6402.8    66.2
#Mann= 6 , 1 , 0
  4167.7      .1       0  4709.5     .12       0  4877.3     .06       0
  5052.7     .12       0  5108.2      .1       0  6053.2      .2       0
Bank Sta=4877.3,5052.7
XS Rating Curve= 0
Exp/Cntr=.3,.1

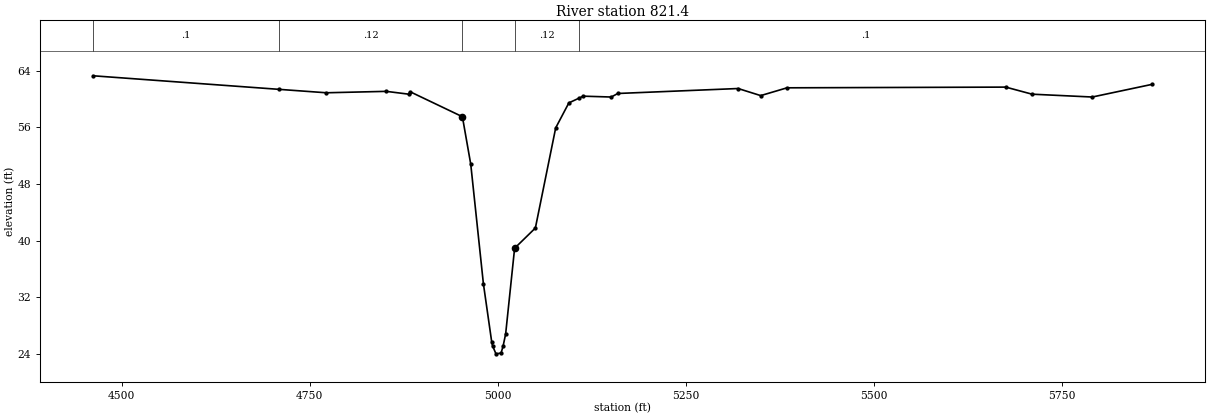
Type RM Length L Ch R = 1 ,821.4   ,0,0,0
BEGIN DESCRIPTION:
Cross Section 821.4
END DESCRIPTION:
XS GIS Cut Line= 5
      3082442.68     13848387.47      3082696.12     13848091.48
      3082763.02     13847811.71      3082787.35     13847276.51
      3082696.39       13847104.
#Sta/Elev= 30
  4461.9    63.3  4709.5   61.38  4771.9    60.9  4851.6    61.1  4881.6    60.7
  4883.6   61.03  4952.8   57.52  4963.9   50.81  4980.7   33.94  4991.8   25.68
    4993   25.14  4997.4   24.03  5004.2   24.14  5006.9   25.12  5010.3   26.85
  5022.2   38.94  5049.8    41.8  5076.8   55.94  5094.3   59.47  5108.2   60.16
  5113.3   60.42  5150.7    60.3  5159.3    60.8  5319.3    61.5  5349.3    60.5
  5384.3    61.6    5675    61.7    5710    60.7    5790    60.3    5870    62.1
#Mann= 5 , 1 , 0
  4461.9      .1       0  4709.5     .12       0  4952.8     .06       0
  5022.2     .12       0  5108.2      .1       0
Bank Sta=4952.8,5022.2
XS Rating Curve= 0
Exp/Cntr=.3,.1

Chan Stop Cuts=-1